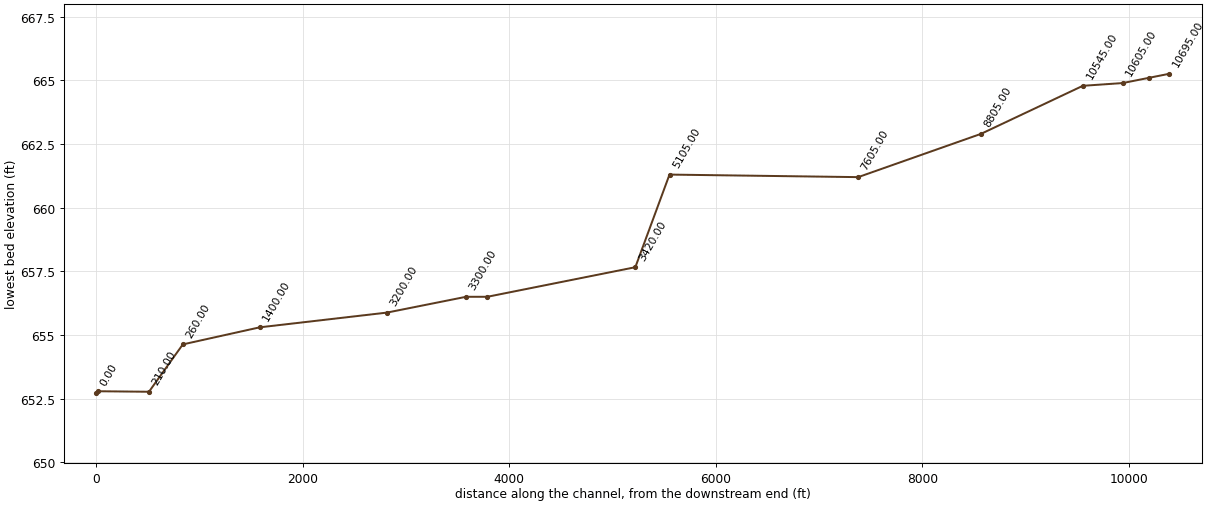
--- SpringCreek.prj (project) ---

Proj Title=SpringCreek
Current Plan=p08
Default Exp/Contr=0.3,0.1
English Units
Geom File=g02
Geom File=g05
Geom File=g06
Geom File=g09
Flow File=f01
Flow File=f02
Flow File=f03
Flow File=f04
Plan File=p01
Plan File=p04
Plan File=p06
Plan File=p08
Y Axis Title=Elevation
X Axis Title(PF)=Main Channel Distance
X Axis Title(XS)=Station
BEGIN DESCRIPTION:
END DESCRIPTION:
DSS Export Rating Curves= 0
DSS Export Rating Curve Sorted= 0
DSS Export Volume Flow Curves= 0
DXF OffsetX= 0
DXF OffsetY= 0
DXF ScaleX= 1
DXF ScaleY= 10

--- SpringCreek.p08 (plan) ---

Plan Title=Natural Conditions
Program Version=5.03
Short Identifier=Natural
Geom File=g09
Flow File=f03
Subcritical Flow
K Sum by GR=-1
Std Step Tol= 0.01
Critical Tol= 0.01
Num of Std Step Trials= 20
Max Error Tol= 0.3
Flow Tol Ratio= 0.001
Split Flow NTrial= 30
Split Flow Tol= 0.02
Split Flow Ratio= 0.02
Log Output Level= 0
Friction Slope Method= 1
Unsteady Friction Slope Method= 2
Unsteady Bridges Friction Slope Method= 1
Parabolic Critical Depth
Global Vel Dist= 0 , 0 , 0
Global Log Level= 0
CheckData=True
Encroach Param=-1 ,0,0, 0
Computation Interval=1MIN
Output Interval=1HOUR
Instantaneous Interval=1HOUR
Mapping Interval=1HOUR
Run HTab= 0
Run UNet= 0
Run Sediment= 0
Run PostProcess= 0
Run WQNet= 0
Run RASMapper= 0
UNET Theta= 1
UNET Theta Warmup= 1
UNET ZTol= 0.02
UNET ZSATol= 0.02
UNET MxIter= 20
UNET Max Iter WO Improvement= 0
UNET MaxInSteps= 0
UNET DtIC= 0
UNET DtMin= 0
UNET MaxCRTS= 20
UNET WFStab= 2
UNET SFStab= 1
UNET WFX= 1
UNET SFX= 1
UNET DSS MLevel= 4
UNET Pardiso=0
UNET DZMax Abort= 100
UNET Use Existing IB Tables=-1
UNET Froude Reduction=False
UNET Froude Limit= 0.8
UNET Froude Power= 4
UNET Time Slicing=0,0, 5
UNET D1 Cores= 0
UNET D2 Coriolis=0
UNET D2 Cores= 0
UNET D2 Theta= 1
UNET D2 Theta Warmup= 1
UNET D2 Z Tol= 0.01
UNET D2 Volume Tol= 0.01
UNET D2 Max Iterations= 20
UNET D2 Equation= 0
UNET D2 RampUpFraction=0.1
UNET D2 TimeSlices= 1
UNET D2 BCVolumeCheck=0
UNET D1D2 MaxIter= 0
UNET D1D2 ZTol=0.01
UNET D1D2 QTol=0.1
UNET D1D2 MinQTol=1
Write IC File= 0
Write IC File at Fixed DateTime=0
Write IC File at Sim End=0
Echo Input=False
Echo Parameters=False
Echo Output=False
Write Detailed= 0
HDF Write Warmup=0
HDF Write Time Slices=0
HDF Flush=0
HDF Face Node Velocities=0
HDF Compression= 1
HDF Chunk Size= 1
HDF Spatial Parts= 1
HDF Use Max Rows=0
HDF Fixed Rows= 1
Calibration Method= 0
Calibration Iterations= 20
Calibration Max Change=0.05
Calibration Tolerance=0.2
Calibration Maximum=1.5
Calibration Minimum=0.5
Calibration Optimization Method= 1
WQ AD Non Conservative
WQ ULTIMATE=-1
WQ Max Comp Step=1HOUR
WQ Output Interval=15MIN
WQ Output Selected Increments= 0
WQ Output face flow=0
WQ Output face velocity=0
WQ Output face area=0
WQ Output face dispersion=0
WQ Output cell volume=0
WQ Output cell surface area=0
WQ Output cell continuity=0
WQ Output cumulative cell continuity=0
WQ Output face conc=0
WQ Output face dconc_dx=0
WQ Output face courant=0
WQ Output face peclet=0
WQ Output face adv mass=0
WQ Output face disp mass=0
WQ Output cell mass=0
WQ Output cell source sink temp=0
WQ Output nsm pathways=0
WQ Output nsm derived pathways=0
WQ Output MaxMinRange=-1
WQ Daily Max Min Mean=-1
WQ Daily Range=0
WQ Daily Time=0
WQ Create Restart=0
WQ Fixed Restart=0
WQ System Summary=0
WQ Write To DSS=0
WQ Use Fixed Temperature=0
Sorting and Armoring Iterations= 10
XS Update Threshold= 0.02
Bed Roughness Predictor= 0
Hydraulics Update Threshold= 0.02
Energy Slope Method= 1
Volume Change Method= 1
Sediment Retention Method= 0
XS Weighting Method= 0
Number of US Weighted Cross Sections= 1
Number of DS Weighted Cross Sections= 1
Upstream XS Weight=0
Main XS Weight=1
Downstream XS Weight=0
Number of DS XS's Weighted with US Boundary= 1
Upstream Boundary Weight= 1
Weight of XSs Associated with US Boundary= 0
Number of US XS's Weighted with DS Boundary= 1
Downstream Boundary Weight= 0.5
Weight of XSs Associated with DS Boundary= 0.5
Percentile Method= 0
Sediment Output Level= 4
Mass or Volume Output= 0
Output Increment Type= 1
Profile and TS Output Increment= 1
XS Output Flag= 0
XS Output Increment= 10
Write Gradation File= 0
Read Gradation Hotstart= 0
Write HDF5 File= 1
Write DSS Sediment File= 0
SV Curve= 0
Specific Gage Flag= 0

--- SpringCreek.p01 (plan) ---

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Plan Title=Duplicate Effective
Short Identifier=Duplicate Effective
Geom File=g02
Flow File=f01

--- SpringCreek.p04 (plan) ---

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Plan Title=Existing
Short Identifier=Existing
Geom File=g05
Flow File=f03

--- SpringCreek.p06 (plan) ---

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Plan Title=Proposed
Short Identifier=Proposed
Geom File=g06
Flow File=f03
K Sum by GR= 0
Calc Critical at every XS

--- SpringCreek.f03 (steady flow) ---

Flow Title=Existing
Program Version=5.03
Number of Profiles= 4
Profile Names=10 YR,50 YR,100 YR,500 YR
River Rch & RM=RIVER-1,Reach-1         ,10695.00
    5625    7425    8125    9750
River Rch & RM=RIVER-1,Reach-1         ,8805.00
    5750    7600    8300    9950
River Rch & RM=RIVER-1,Reach-1         ,7605.00
    5875    7775    8475   10175
River Rch & RM=RIVER-1,Reach-1         ,5105.00
    6075    8050    8775   10500
River Rch & RM=RIVER-1,Reach-1         ,3420.00
    7075    9425   10275   12375
River Rch & RM=RIVER-1,Reach-1         ,1400.00
    7175    9525   10375   12400
River Rch & RM=RIVER-1,Reach-1         ,260.00
    7250    9600   10450   12450
Boundary for River Rch & Prof#=RIVER-1,Reach-1         , 1
Up Type= 0
Dn Type= 1
Dn Known WS=672.75
Boundary for River Rch & Prof#=RIVER-1,Reach-1         , 2
Up Type= 0
Dn Type= 1
Dn Known WS=674.94
Boundary for River Rch & Prof#=RIVER-1,Reach-1         , 3
Up Type= 0
Dn Type= 1
Dn Known WS=676.5
Boundary for River Rch & Prof#=RIVER-1,Reach-1         , 4
Up Type= 0
Dn Type= 1
Dn Known WS=681.6
DSS Import GetInterval= 0
DSS Import GetPeak= 0
DSS Import FillOption= 0

--- SpringCreek.f01 (steady flow) ---

Flow Title=Duplicate Effective
Program Version=5.03
Number of Profiles= 4
Profile Names=10 YR,50 YR,100 YR,500 YR
River Rch & RM=RIVER-1,Reach-1         ,18824.00
    4600    6300    6700    8350
River Rch & RM=RIVER-1,Reach-1         ,17504.00
    4800    6500    7150    8600
River Rch & RM=RIVER-1,Reach-1         ,15339.00
    5250    6900    7500    9150
River Rch & RM=RIVER-1,Reach-1         ,15075.00
    5300    7000    7650    9200
River Rch & RM=RIVER-1,Reach-1         ,12375.00
    5500    7275    7950    9550
River Rch & RM=RIVER-1,Reach-1         ,10695.00
    5625    7425    8125    9750
River Rch & RM=RIVER-1,Reach-1         ,8805.00
    5750    7600    8300    9950
River Rch & RM=RIVER-1,Reach-1         ,7605.00
    5875    7775    8475   10175
River Rch & RM=RIVER-1,Reach-1         ,5105.00
    6075    8050    8775   10500
River Rch & RM=RIVER-1,Reach-1         ,3420.00
    7075    9425   10275   12375
River Rch & RM=RIVER-1,Reach-1         ,1400.00
    7175    9525   10375   12400
River Rch & RM=RIVER-1,Reach-1         ,260.00
    7250    9600   10450   12450
Boundary for River Rch & Prof#=RIVER-1,Reach-1         , 1
Up Type= 0
Dn Type= 1
Dn Known WS=672.7
Boundary for River Rch & Prof#=RIVER-1,Reach-1         , 2
Up Type= 0
Dn Type= 1
Dn Known WS=674.9
Boundary for River Rch & Prof#=RIVER-1,Reach-1         , 3
Up Type= 0
Dn Type= 1
Dn Known WS=676.5
Boundary for River Rch & Prof#=RIVER-1,Reach-1         , 4
Up Type= 0
Dn Type= 1
Dn Known WS=681.6
DSS Import GetInterval= 0
DSS Import GetPeak= 0
DSS Import FillOption= 0

--- SpringCreek.f02 (steady flow) ---

Flow Title=Imported Flow 02
Program Version=5.03
Number of Profiles= 1
Profile Names=PF 1
River Rch & RM=RIVER-1,Reach-1         ,32
    4600
River Rch & RM=RIVER-1,Reach-1         ,31
    4800
River Rch & RM=RIVER-1,Reach-1         ,30
    5250
River Rch & RM=RIVER-1,Reach-1         ,29
    5300
River Rch & RM=RIVER-1,Reach-1         ,28
    5500
River Rch & RM=RIVER-1,Reach-1         ,22
    5625
River Rch & RM=RIVER-1,Reach-1         ,16
    5750
River Rch & RM=RIVER-1,Reach-1         ,15
    5875
River Rch & RM=RIVER-1,Reach-1         ,14
    6075
River Rch & RM=RIVER-1,Reach-1         ,13
    7075
River Rch & RM=RIVER-1,Reach-1         ,7
    7175
River Rch & RM=RIVER-1,Reach-1         ,6
    7250
Boundary for River Rch & Prof#=RIVER-1,Reach-1         , 1
Up Type= 0
Dn Type= 0
DSS Import GetInterval= 0
DSS Import GetPeak= 0
DSS Import FillOption= 0

--- SpringCreek.f04 (steady flow) ---

Flow Title=Existing - Normal Depth
Program Version=5.03
Number of Profiles= 4
Profile Names=10 YR,50 YR,100 YR,500 YR
River Rch & RM=RIVER-1,Reach-1         ,10695.00
    5625    7425    8125    9750
River Rch & RM=RIVER-1,Reach-1         ,8805.00
    5750    7600    8300    9950
River Rch & RM=RIVER-1,Reach-1         ,7605.00
    5875    7775    8475   10175
River Rch & RM=RIVER-1,Reach-1         ,5105.00
    6075    8050    8775   10500
River Rch & RM=RIVER-1,Reach-1         ,3420.00
    7075    9425   10275   12375
River Rch & RM=RIVER-1,Reach-1         ,1400.00
    7175    9525   10375   12400
River Rch & RM=RIVER-1,Reach-1         ,260.00
    7250    9600   10450   12450
Boundary for River Rch & Prof#=RIVER-1,Reach-1         , 1
Up Type= 0
Dn Type= 3
Dn Slope=0.001
Boundary for River Rch & Prof#=RIVER-1,Reach-1         , 2
Up Type= 0
Dn Type= 3
Dn Slope=0.001
Boundary for River Rch & Prof#=RIVER-1,Reach-1         , 3
Up Type= 0
Dn Type= 3
Dn Slope=0.001
Boundary for River Rch & Prof#=RIVER-1,Reach-1         , 4
Up Type= 0
Dn Type= 3
Dn Slope=0.001
DSS Import GetInterval= 0
DSS Import GetPeak= 0
DSS Import FillOption= 0

--- SpringCreek.g09 (geometry) ---

Geom Title=Natural Conditions
Program Version=5.03

River Reach=RIVER-1         ,Reach-1
Reach XY= 2
             0.5            0.95             0.5            0.05

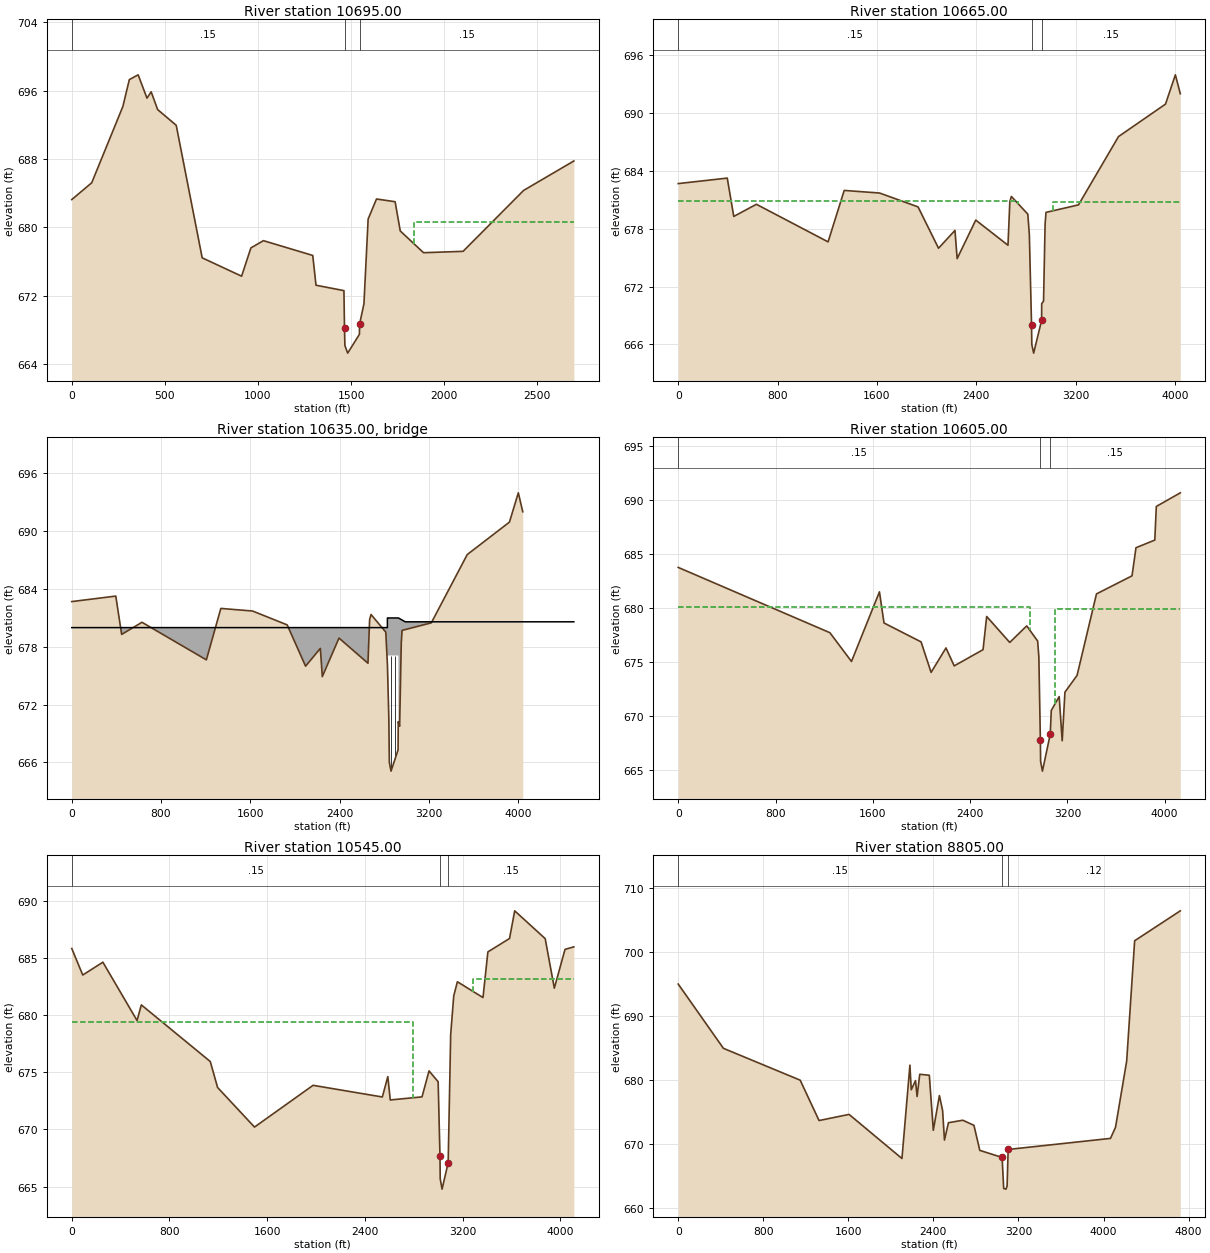
Type RM Length L Ch R = 1 ,10695.00,186.89,198.93,209.3
BEGIN DESCRIPTION:
2.26 (D)
END DESCRIPTION:
#Sta/Elev= 30
       0  683.24   107.2  685.21  274.24  694.13  309.14  697.29  356.51  697.85
  403.88  695.12  426.32  695.86  461.22  693.78  560.93  691.94  700.38  676.42
  912.06  674.27  961.86  677.58 1029.16  678.43 1294.09   676.7 1311.58  673.21
 1461.55  672.58 1464.66  668.16 1466.66  666.16 1481.66  665.26 1544.66  667.46
 1545.66  668.66 1569.02  671.04 1591.51  680.96  1636.5  683.31 1736.48  682.99
 1763.97  679.57 1888.94  677.02 2101.38  677.18 2426.28  684.31  2696.2  687.76
#Mann= 3 , 0 , 0
       0     .15       0 1464.66    .045       0 1545.66     .15       0
#XS Ineff= 1 ,-1
 1837.59 2694.51680.6383
Permanent Ineff=
       F
Bank Sta=1464.66,1545.66
XS Rating Curve= 0 ,0
Sediment Elevation=0
Exp/Cntr=0.5,0.3

Type RM Length L Ch R = 1 ,10665.00,253.15,253.39,255.24
BEGIN DESCRIPTION:
2.26 (Ringgold Road US)
END DESCRIPTION:
#Sta/Elev= 30
       0   682.7  394.63  683.27  447.08  679.29  629.41  680.55 1206.38  676.65
 1336.26  681.99    1621  681.72 1930.73  680.28 2095.59  675.99 2227.98  677.84
 2245.46  674.91 2395.28  678.91 2654.73   676.3  2669.7  680.84 2682.17  681.36
 2814.33  679.53 2826.75   677.4 2844.47     668 2846.47     666 2861.47   665.1
 2925.47   668.5 2926.14  670.23 2941.05   670.5 2953.47  678.47 2960.93  679.71
 3222.42  680.49 3544.52  687.58 3922.82  690.95 4002.34  693.99  4042.1  692.03
#Mann= 3 , 0 , 0
       0     .15       0 2844.47    .045       0 2925.47     .15       0
#XS Ineff= 2 ,-1
       0 2737.76680.9302 3013.21  4042.1680.7602
Permanent Ineff=
       F       F
Bank Sta=2844.47,2925.47
XS Rating Curve= 0 ,0
Sediment Elevation=0
Exp/Cntr=0.5,0.3

Type RM Length L Ch R = 3 ,10635.00,,,
BEGIN DESCRIPTION:
Ringgold Road
END DESCRIPTION:
Bridge Culvert--1,0,-1,-1, 0
Deck Dist Width WeirC Skew NumUp NumDn MinLoCord MaxHiCord MaxSubmerge Is_Ogee
75,90,2.6,0, 11, 11, , , 0.98, 0, 0,0,,
       0 2608.83 2728.83 2828.83 2828.83 2831.83 2831.83 2927.83 2927.83 2988.83
    4500
     680     680     680     680     681     681     681     681     681   680.6
   680.6
       0       0       0       0       0       0   677.1   677.1       0       0
       0
       0 2748.81 2868.81 2968.81 2968.81 2971.81 2971.81 3067.81 3067.81 3128.81
    4500
     680     680     680     680     681     681     681     681     681   680.6
   680.6
       0       0       0       0       0       0   677.1   677.1       0       0
       0
Pier Skew, UpSta & Num, DnSta & Num=  ,2864.33, 2 ,3004.31, 2 , 0 , 0 , 0 ,,
       1       1
   665.1   677.1
       1       1
   665.1   677.1
Pier Skew, UpSta & Num, DnSta & Num=  ,2896.33, 2 ,3033.91, 2 , 0 , 0 , 0 ,,
       1       1
   666.1   677.1
       1       1
   666.1   677.1
BR Coef=-1 , 1 , 0 ,, 0 ,,,0.8,0,2,0,
WSPro=,,,, 1 ,,,, 0 ,,,, 0 ,,,,-1 ,-1 ,-1 , 0 , 0 , 0 , 0 , 0
BR U #Sta/Elev= 30
       0   682.7  394.63  683.27  447.08  679.29  629.41  680.55 1206.38  676.65
 1336.26  681.99    1621  681.72 1930.73  680.28 2095.59  675.99 2227.98  677.84
 2245.46  674.91 2395.28  678.91 2654.73   676.3  2669.7  680.84 2682.17  681.36
 2814.33  679.53 2829.47  676.09 2841.66  670.66 2846.47     666 2861.47   665.1
 2924.47   667.3 2926.14  670.23 2938.56  669.77 2953.47  678.47 2960.93  679.71
 3222.42  680.49 3544.52  687.58 3922.82  690.95 4002.34  693.99  4042.1  692.03
BR U #Mann= 3
       0     .15 2829.47    .045 2926.14     .15
BR U Banks=2829.47,2926.14
BR D #Sta/Elev= 30
       0  683.74 1247.25   677.7 1424.72  675.04 1654.67  681.48 1692.17   678.6
 1996.95  676.85 2079.39  674.03  2201.8  676.29 2269.25  674.63 2506.51  676.13
 2536.44   679.2 2725.99   676.8 2865.65  678.33 2955.43  676.93 2965.41  675.47
 2972.89  670.18 2979.88 665.795 2994.88 664.895 3057.88 667.095 3067.66  670.51
 3132.51  671.79 3157.45   667.7 3179.89   672.2 3279.65  673.75 3439.37  681.29
 3731.57  682.96 3764.04  685.56 3918.88  686.27 3931.36  689.38 4128.66  690.64
BR D #Mann= 3
       0     .15 2972.89    .045 3067.66     .15
BR D Banks=2972.89,3067.66
BC Design=,, 0 ,, 0 ,,,,,,
BC Use User HTab Curves=0
BC User HTab FreeFlow(D)= 0

Type RM Length L Ch R = 1 ,10605.00,381.8,386.1,399.22
BEGIN DESCRIPTION:
2.26 (Ringgold Road DS)
END DESCRIPTION:
#Sta/Elev= 30
       0  683.74 1247.25   677.7 1424.72  675.04 1654.67  681.48 1692.17   678.6
 1996.95  676.85 2079.39  674.03  2201.8  676.29 2269.25  674.63 2506.51  676.13
 2536.44   679.2 2725.99   676.8 2865.65  678.33 2955.43  676.93 2965.41  675.47
 2977.88 667.795 2979.88 665.795 2994.88 664.895 3058.88 668.295 3067.66  670.51
 3132.51  671.79 3157.45   667.7 3179.89   672.2 3279.65  673.75 3439.37  681.29
 3731.57  682.96 3764.04  685.56 3918.88  686.27 3931.36  689.38 4128.66  690.64
#Mann= 3 , 0 , 0
       0     .15       0 2977.88    .045       0 3058.88     .15       0
#XS Ineff= 2 ,-1
       0 2892.38680.0463 3098.24 4128.66679.9157
Permanent Ineff=
       F       F
Bank Sta=2977.88,3058.88
XS Rating Curve= 0 ,0
Sediment Elevation=0
Exp/Cntr=0.5,0.3

Type RM Length L Ch R = 1 ,10545.00,832.89,986.24,1029.87
BEGIN DESCRIPTION:
2.26
END DESCRIPTION:
#Sta/Elev= 30
       0  685.82   89.92   683.5  254.78  684.62  534.53  679.52   569.5  680.89
 1134.01  675.94 1193.96  673.67 1496.19  670.21 1975.77  673.86 2542.82  672.84
  2587.8  674.62 2607.79  672.58 2867.69  672.85 2925.17  675.12 2999.81  674.17
 3014.81 667.687 3016.81 665.687 3031.81 664.787 3081.81 667.087 3102.43   678.3
  3127.4  681.67 3157.35  682.91 3367.02  681.53 3406.96  685.52 3584.18  686.69
 3626.61  689.11 3876.22  686.68  3951.1  682.35 4038.46  685.74 4110.85  685.96
#Mann= 3 , 0 , 0
       0     .15       0 3014.81    .045       0 3081.81     .15       0
#XS Ineff= 2 ,-1
 3288.71 4110.85683.1309       0 2790.59679.4107
Permanent Ineff=
       F       F
Bank Sta=3014.81,3081.81
XS Rating Curve= 0 ,0
Sediment Elevation=0
Exp/Cntr=0.3,0.1

Type RM Length L Ch R = 1 ,8805.00 ,1296.84,1189.66,1081.94
BEGIN DESCRIPTION:
1.92
END DESCRIPTION:
#Sta/Elev= 30
       0  694.95  424.83  684.91 1147.05  679.93 1324.48  673.62 1606.87  674.58
 2104.17  667.69 2179.14  682.28 2191.64  678.43 2231.62  679.86 2246.62  677.38
 2271.61  680.85 2361.57   680.7 2399.06   672.1 2456.53  677.52 2486.52  675.19
 2504.01  670.57  2541.5  673.28 2676.45  673.67 2781.41  672.87 2836.39  668.96
 3046.32  667.85 3061.13     663 3083.13   662.9 3093.13   663.4 3103.13   669.1
 4065.55  670.83 4112.99  672.57 4217.88  682.92 4292.79  701.72 4722.31   706.4
#Mann= 3 , 0 , 0
       0     .15       0 3046.32    .045       0 3103.13     .12       0
#XS Ineff= 2 , 0
Permanent Ineff=
       F       F
Bank Sta=3046.32,3103.13
XS Rating Curve= 0 ,0
Sediment Elevation=0
Exp/Cntr=0.3,0.1

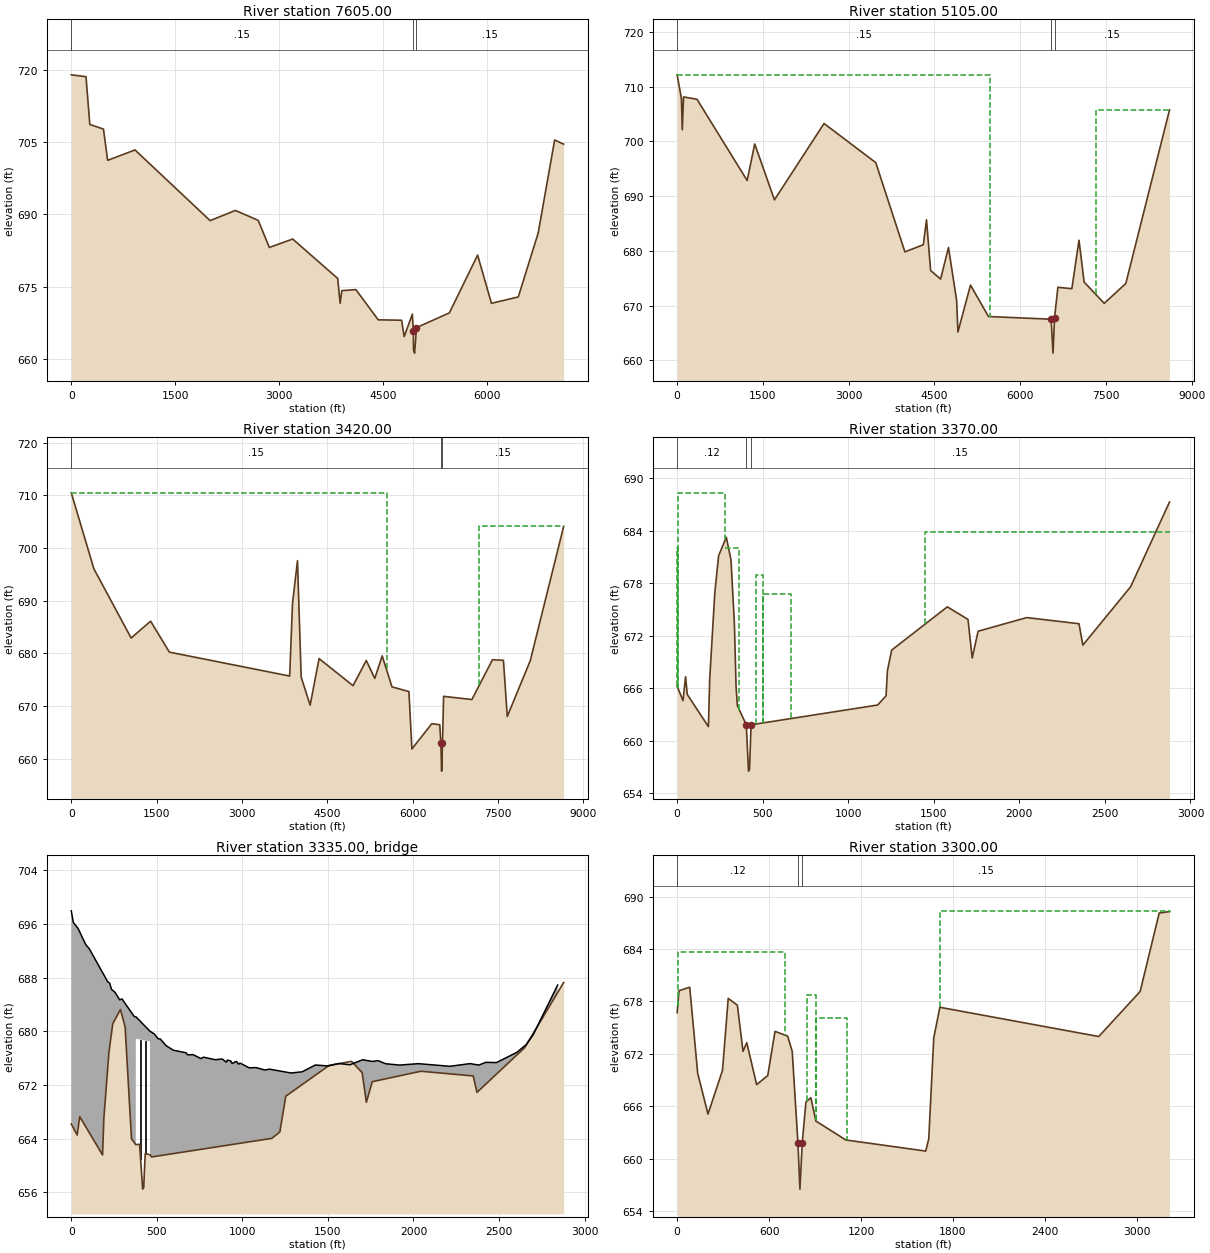
Type RM Length L Ch R = 1 ,7605.00 ,1917.65,1827.59,1722.48
BEGIN DESCRIPTION:
1.6
END DESCRIPTION:
#Sta/Elev= 30
       0     719  212.42  718.61   267.4   708.7  464.82  707.73   524.8  701.24
  919.65   703.4 2004.26  688.72 2369.12  690.83    2699  688.77 2858.94  683.14
 3196.32   684.9 3846.08  676.71 3881.07  671.56 3906.06  674.18 4108.49  674.39
 4430.91  668.12 4768.38  668.03 4805.88  664.63 4923.37  669.29 4938.37   665.8
 4940.37   661.9 4956.37   661.2 4983.37   666.5 5458.33  669.56 5865.72  681.56
 6065.66  671.55 6453.04  672.87 6740.46  686.16 6977.88  705.46 7107.85   704.6
#Mann= 3 , 0 , 0
       0     .15       0 4938.37    .045       0 4983.37     .15       0
#XS Ineff= 2 , 0
Permanent Ineff=
       F       F
Bank Sta=4938.37,4983.37
XS Rating Curve= 0 ,0
Sediment Elevation=0
Exp/Cntr=0.3,0.1

Type RM Length L Ch R = 1 ,5105.00 ,317.2,331.08,338.51
BEGIN DESCRIPTION:
1.07
END DESCRIPTION:
#Sta/Elev= 30
       0  712.18   74.98  707.87   89.97  702.14  112.47  708.14   347.4  707.71
 1224.64  692.86  1357.1  699.54    1702  689.32 2569.24  703.28 3473.96  696.13
 3983.81  679.81 4306.21  681.12 4361.19  685.68 4433.67   676.4 4608.56  674.84
 4745.97  680.62 4888.38  670.94 4910.87  665.16 5130.73  673.74 5445.53  667.99
 6541.28   667.5 6574.28   661.3 6601.28   667.8 6659.36  673.34  6903.8  673.08
 7028.51  681.94  7118.3  674.29 7470.14   670.4 7847.21  674.03 8611.33  705.77
#Mann= 3 , 0 , 0
       0     .15       0 6541.28    .045       0 6601.28     .15       0
#XS Ineff= 2 ,-1
       0 5476.14 712.179  7321.5 8611.33705.7676
Permanent Ineff=
       F       F
Bank Sta=6541.28,6601.28
XS Rating Curve= 0 ,0
Sediment Elevation=0
Exp/Cntr=0.3,0.1

Type RM Length L Ch R = 1 ,3420.00 ,1149.97,1433.95,1398.9
BEGIN DESCRIPTION:
0.7 (C)
END DESCRIPTION:
#Sta/Elev= 30
       0  710.49   397.5  696.06  1052.5  682.93    1395  686.12 1725.01  680.25
 3839.86  675.71 3889.84  689.51  3977.3   697.6 4042.26   675.5 4199.68  670.19
  4357.1  679.02 4954.28  673.88 5186.66  678.66 5336.58  675.26 5466.51  679.54
 5638.93  673.66 5936.39  672.76 5988.88  661.87 6338.84  666.66 6478.83  666.47
 6498.82662.9615 6511.82657.6615 6526.82662.9615 6546.32  671.86 7043.76  671.25
  7406.2  678.82 7598.48  678.69 7665.91  668.04 8070.45  678.63 8657.27  704.12
#Mann= 3 , 0 , 0
       0     .15       0 6498.82    .045       0 6526.82     .15       0
#XS Ineff= 2 ,-1
       0 5547.66710.4872 7173.32 8657.27704.1202
Permanent Ineff=
       F       F
Bank Sta=6498.82,6526.82
XS Rating Curve= 0 ,0
Sediment Elevation=0
Exp/Cntr=0.5,0.3

Type RM Length L Ch R = 1 ,3370.00 ,212.33,205.56,203.38
BEGIN DESCRIPTION:
0.7 (Spring Creek Road US)
END DESCRIPTION:
#Sta/Elev= 30
       0   666.2   34.56  664.56   49.38  667.29   59.25  665.27  182.88  661.59
  190.34  667.02  220.18   676.9  242.55  681.14   287.3  683.25  314.65  680.67
  334.54  673.42  344.49  666.17  351.95     664  404.16   661.8  417.16   656.5
  423.16   656.7  432.16   661.8 1171.86  664.06 1221.09  665.11 1228.95  667.96
 1253.77  670.34 1579.27  675.29 1699.99  673.85 1724.62  669.44 1759.11   672.5
 2043.22  674.06 2348.86  673.36 2371.23  670.91 2650.66  677.59 2877.71  687.28
#Mann= 3 , 0 , 0
       0     .12       0  404.16    .045       0  432.16     .15       0
#XS Ineff= 6 ,-1
     3.4  282.31  688.33 1450.68 2877.71  683.84  282.31  362.97  681.99
       0     3.4  681.99  461.34   504.5   678.9   504.5  666.65   676.8
Permanent Ineff=
       F       F       F       F       F       F
Bank Sta=404.16,432.16
XS Rating Curve= 0 ,0
Sediment Elevation=0
Exp/Cntr=0.5,0.3

Type RM Length L Ch R = 3 ,3335.00 ,,,
BEGIN DESCRIPTION:
Spring Creek Road
END DESCRIPTION:
Bridge Culvert--1,0,-1,-1, 0
Deck Dist Width WeirC Skew NumUp NumDn MinLoCord MaxHiCord MaxSubmerge Is_Ogee
67,60,2.6,0, 60, 60, , , 0.98, 0, 0,0,,
       0   11.95   39.58   84.64  105.62  212.47  224.62  234.78   256.1  282.94
  296.08     369  377.16  377.16  460.16  460.16  485.01  507.88  519.75  553.41
  595.75  671.34   679.7  712.07  757.92  772.76  840.89  882.57  905.95  912.35
  931.08  940.16  964.86  978.22  987.13 1039.87 1079.35 1130.55 1159.34 1284.01
 1349.39 1426.81 1500.69 1563.93  1628.5 1702.45 1761.27 1791.25 1837.52 1917.97
  2028.8 2212.87 2331.06 2381.41 2422.81 2484.91 2603.74 2658.51 2699.34 2842.74
  697.96  696.23  695.34  692.93  692.29  687.41  687.17  686.27  685.81  684.69
  684.84  682.18  682.19  682.19  680.02  680.02  679.63  678.89  678.88  677.89
   677.2  676.81  676.51  676.53  675.95  676.16  675.78  675.88  675.41  675.72
  675.61  675.22  675.53  675.12  675.27  674.57  674.61  674.25  674.37   673.8
  673.98  674.99  674.85  675.21  675.03  675.77  675.52  675.65  675.18  674.98
  675.19   674.8   675.2  674.98  675.39  675.35  676.87  678.02  679.49   686.9
       0       0       0       0       0       0       0       0       0       0
       0       0       0   678.9   678.5       0       0       0       0       0
       0       0       0       0       0       0       0       0       0       0
       0       0       0       0       0       0       0       0       0       0
       0       0       0       0       0       0       0       0       0       0
       0       0       0       0       0       0       0       0       0       0
       0   12.76   38.38   94.43  133.15  181.79  230.63  323.18  420.44   465.5
  486.48  593.33  605.48  615.64  636.96   663.8  676.94  749.86  758.02  758.02
  841.02  841.02  865.87  888.74  900.61  934.27  976.61  1052.2 1060.56 1092.93
 1138.78 1153.62 1221.75 1263.43 1286.81 1293.21 1311.94 1321.02 1345.72 1359.08
 1367.99 1420.73  1540.2 1664.87 1730.25 1807.67 1881.55 1944.79 2009.36 2083.31
 2172.11 2218.38 2298.83 2409.66 2593.73 2865.77  2984.6 3039.37  3080.2  3223.6
   693.7  694.64  695.31  697.43  698.12  698.68  698.76  697.96  695.34  692.93
  692.29  687.41  687.17  686.27  685.81  684.69  684.84  682.18  682.19  682.19
  680.02  680.02  679.63  678.89  678.88  677.89   677.2  676.81  676.51  676.53
  675.95  676.16  675.78  675.88  675.41  675.72  675.61  675.22  675.53  675.12
  675.27  674.57  674.37   673.8  673.98  674.99  674.85  675.21  675.03  675.77
  675.65  675.18  674.98  675.19   674.8  675.35  676.87  678.02  679.49   686.9
       0       0       0       0       0       0       0       0       0       0
       0       0       0       0       0       0       0       0       0   678.9
   678.5       0       0       0       0       0       0       0       0       0
       0       0       0       0       0       0       0       0       0       0
       0       0       0       0       0       0       0       0       0       0
       0       0       0       0       0       0       0       0       0       0
Pier Skew, UpSta & Num, DnSta & Num=  ,405.16, 2 ,786.02, 2 , 0 , 0 , 0 ,,
       2       2
   661.8   678.8
       2       2
   661.8   678.8
Pier Skew, UpSta & Num, DnSta & Num=  ,433.16, 2 ,814.02, 2 , 0 , 0 , 0 ,,
       2       2
   661.8   678.7
       2       2
   661.8   678.7
BR Coef=-1 , 1 , 0 ,, 0 ,,,0.8,0,2,0,
WSPro=,,,, 1 ,,,, 0 ,,,, 0 ,,,,-1 ,-1 ,-1 , 0 , 0 , 0 , 0 , 0
BR U #Sta/Elev= 30
       0   666.2   34.56  664.56   49.38  667.29  182.88  661.59  190.34  667.02
  220.18   676.9  242.55  681.14   287.3  683.25  314.65  680.67  351.95     664
  376.81  663.13  399.18  663.18  417.16   656.5  423.16   656.7  432.16   661.8
  461.34   661.6   468.8  661.29 1171.86  664.06 1219.02  665.02 1253.77  670.34
 1507.73  674.94  1638.4  675.53 1699.99  673.85 1724.62  669.44 1759.11   672.5
 2043.22  674.06 2348.86  673.36 2371.23  670.91 2650.66  677.59 2877.71  687.28
BR U #Mann= 3
       0     .12  376.81    .045   468.8     .15
BR U Banks=376.81,461.34
BR D #Sta/Elev= 30
       0  676.71   12.44  679.23   82.11  679.63  134.36  669.75  201.54   665.1
  296.09   670.1  333.42  678.35  393.13  677.57  429.92  672.28  454.31  673.28
     519  668.47  573.93  671.23  591.41  669.51  638.85  674.57  751.14  672.28
     776   666.8  801.43   656.5  840.64  666.48  843.13  666.52 1165.52  661.66
 1310.26  663.55 1622.24  660.86 1642.23  662.25 1674.71  673.79 1714.68  677.33
 2504.09  676.45 2751.82  673.98 3021.96  679.14 3146.31  688.13 3213.46  688.29
BR D #Mann= 3
       0     .12  751.14    .045  843.13     .15
BR D Banks=751.14,840.64
BC Design=,, 0 ,, 0 ,,,,,,
BC Use User HTab Curves=0
BC User HTab FreeFlow(D)= 0

Type RM Length L Ch R = 1 ,3300.00 ,676.12,766.4,761.35
BEGIN DESCRIPTION:
0.7 (Spring Creek Road DS)
END DESCRIPTION:
#Sta/Elev= 30
       0  676.71   12.44  679.23   82.11  679.63  134.36  669.75  201.54   665.1
  296.09   670.1  333.42  678.35  393.13  677.57  429.92  672.28  454.31  673.28
     519  668.47  591.41  669.51  638.85  674.57  721.25  674.03  751.14  672.28
  788.43   661.8  801.43   656.5  816.43   661.8  840.64  666.48  872.96  666.97
  905.28   664.3 1101.23  662.13 1622.24  660.86 1642.23  662.25 1674.71  673.79
 1714.68  677.33 2751.82  673.98 3021.96  679.14 3146.31  688.13 3213.46  688.29
#Mann= 3 , 0 , 0
       0     .12       0  788.43    .045       0  816.43     .15       0
#XS Ineff= 4 ,-1
 1716.27 3213.46  688.38    3.97   701.9 683.698  845.73  904.45   678.7
  904.45 1107.53  676.11
Permanent Ineff=
       F       F       F       F
Bank Sta=788.43,816.43
XS Rating Curve= 0 ,0
Sediment Elevation=0
Exp/Cntr=0.5,0.3

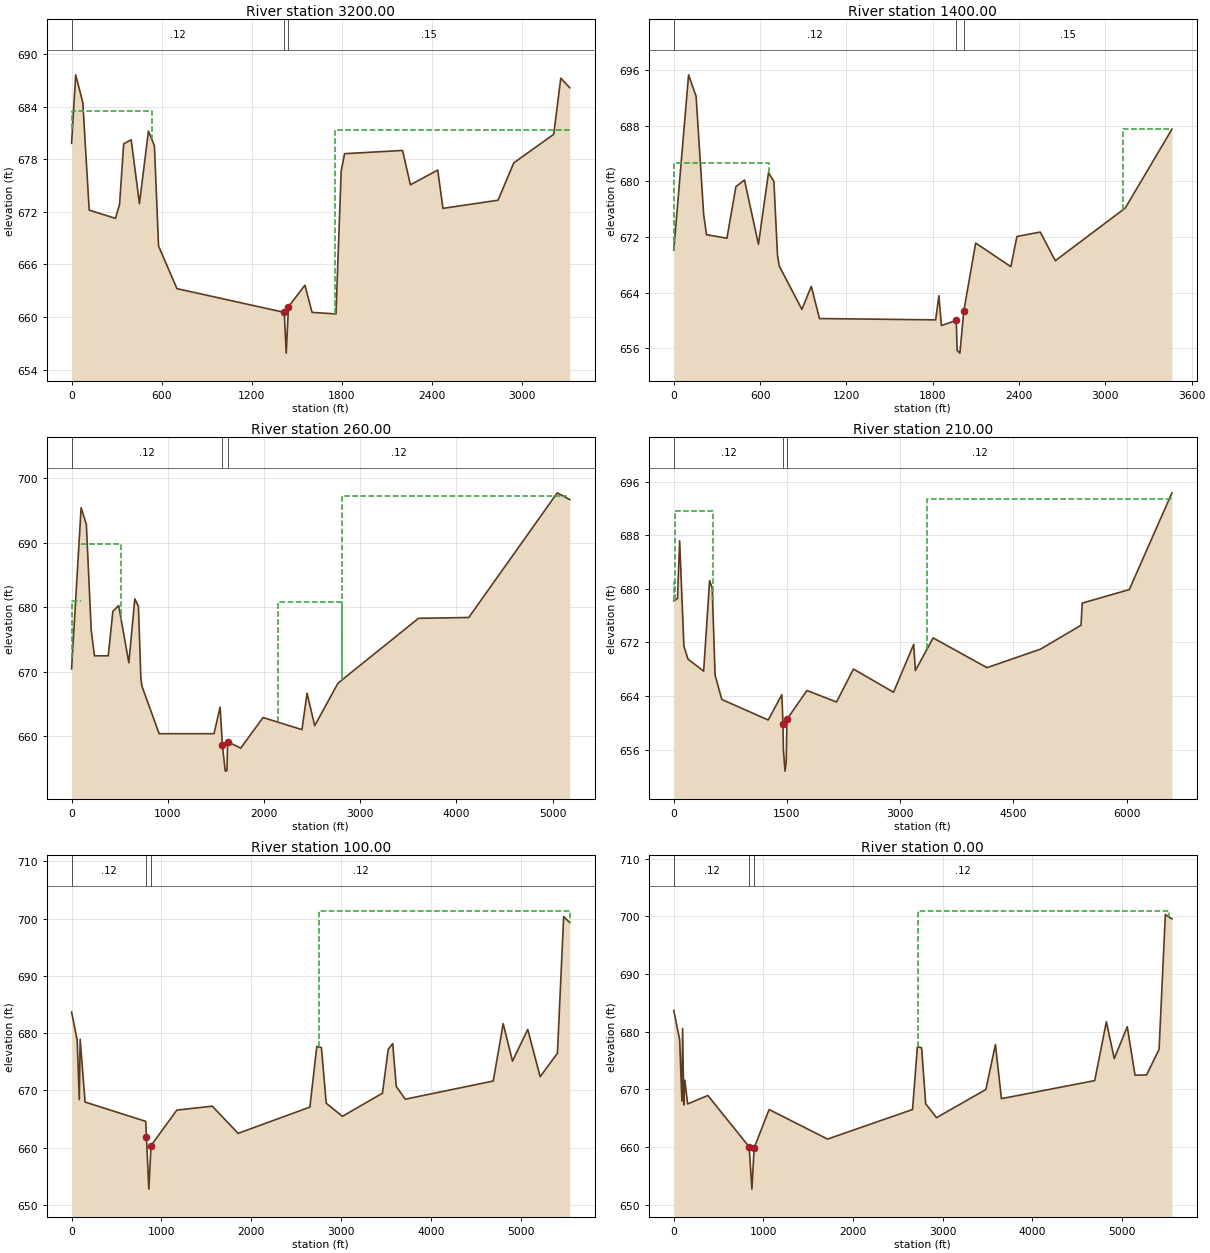
Type RM Length L Ch R = 1 ,3200.00 ,984.35,1233.17,1207.34
BEGIN DESCRIPTION:
0.7
END DESCRIPTION:
#Sta/Elev= 30
       0  679.82   27.49  687.64   74.98  684.48  117.46   672.2  292.41  671.26
   319.9  672.85  347.39  679.77  397.37  680.23  452.36  672.94  512.34  681.22
  552.33  679.54  579.82  668.11  702.28  663.24 1417.77  660.53 1430.77 655.879
 1445.77 661.179 1555.57  663.63 1602.91  660.53 1762.38  660.35 1797.26  676.66
 1819.68  678.64 2206.22  679.01 2258.59  675.09 2440.65  676.77 2475.61   672.4
 2842.67  673.33 2947.53  677.59 3213.78  680.85 3261.05  687.26 3320.77  686.16
#Mann= 3 , 0 , 0
       0     .12       0 1417.77    .045       0 1445.77     .15       0
#XS Ineff= 2 ,-1
    5.95  534.88683.5193 1757.28 3320.77681.3709
Permanent Ineff=
       F       F
Bank Sta=1417.77,1445.77
XS Rating Curve= 0 ,0
Sediment Elevation=0
Exp/Cntr=0.3,0.1

Type RM Length L Ch R = 1 ,1400.00 ,685.15,743.98,767.45
BEGIN DESCRIPTION:
0.32 (B)
END DESCRIPTION:
#Sta/Elev= 30
       0  670.11  102.99   695.3  155.31   692.2  207.64  675.27  227.57  672.32
   369.6  671.82  431.89  679.23  491.63  680.18  588.66  670.94  658.58  681.22
  696.05  679.98  721.02  669.39  733.51   667.8  890.84  661.59  955.77   664.9
 1013.21  660.27 1820.47  660.08 1842.96  663.55 1860.46  659.27  1963.9     660
  1969.9   655.7  1988.9   655.3 2016.45   661.4 2098.73  671.12 2343.08  667.73
 2385.47  672.07 2547.54   672.7 2652.27  668.58 3138.71  676.16    3463  687.49
#Mann= 3 , 0 , 0
       0     .12       0  1963.9    .045       0 2016.45     .15       0
#XS Ineff= 2 ,-1
 3120.78    3463687.4935       0  660.38682.5823
Permanent Ineff=
       F       F
Bank Sta=1963.9,2016.45
XS Rating Curve= 0 ,0
Sediment Elevation=0
Exp/Cntr=0.3,0.1

Type RM Length L Ch R = 1 ,260.00  ,340.4,327.95,308.81
BEGIN DESCRIPTION:
0.08 (A)
END DESCRIPTION:
#Sta/Elev= 30
       0  670.46   99.26  695.43  153.68  692.86  204.04  676.49  237.76  672.49
  381.52   672.5  429.23  679.39  489.77  680.28  595.26  671.41  657.38  681.32
  694.94  680.16  720.32  669.03  731.89  667.77  910.35  660.43 1480.69  660.43
 1544.25  664.55 1567.75  658.63 1597.52  654.63 1614.99   654.7 1621.89  659.19
 1758.21  658.19 1990.49  662.93 2395.13  661.06 2447.58   666.7 2527.51  661.67
 2769.76  668.26 3606.31   678.3 4128.73  678.43  5048.6  697.74 5178.59  696.69
#Mann= 3 , 0 , 0
       0     .12       0 1567.75    .045       0 1621.89     .12       0
#XS Ineff= 5 ,-1
     6.8   95.24681.0101   95.24  517.01  689.89 2149.66 2809.81680.7996
 2809.81 5135.17  697.28 5135.17 5178.59680.7996
Permanent Ineff=
       F       F       F       F       F
Bank Sta=1567.75,1621.89
XS Rating Curve= 0 ,0
Sediment Elevation=0
Exp/Cntr=0.5,0.3

Type RM Length L Ch R = 1 ,210.00  ,499.99,491.72,481.81
BEGIN DESCRIPTION:
0.08 (I75 US)
END DESCRIPTION:
#Sta/Elev= 30
       0  678.22   49.39  678.55   77.76   687.2  134.43  671.45  188.51  669.51
  395.81  667.72  474.67  681.24   509.7  680.12  547.36  667.11  636.41  663.48
 1251.07  660.41 1432.08   664.2 1447.17  659.79 1452.55  655.91 1474.44  652.77
  1489.9  654.21 1499.13  660.52  1764.3  664.82 2156.39   663.1 2380.94  668.03
 2911.17  664.56 3178.76  671.71  3200.9  667.79 3435.96  672.68 4150.11  668.23
 4858.96     671 5395.72  674.57  5411.1  677.88 6035.03   679.9 6600.01  694.36
#Mann= 3 , 0 , 0
       0     .12       0 1447.17    .045       0 1499.13     .12       0
#XS Ineff= 3 ,-1
       0    11.9   681.1    11.9  515.87  691.65 3357.66 6597.64  693.38
Permanent Ineff=
       F       F       F
Bank Sta=1447.17,1499.13
XS Rating Curve= 0 ,0
Sediment Elevation=0
Exp/Cntr=0.5,0.3

Type RM Length L Ch R = 1 ,100.00  ,17.76,17.86,21.41
BEGIN DESCRIPTION:
0.08 (I75 DS)
END DESCRIPTION:
#Sta/Elev= 30
       0  683.68   62.31   678.8   86.02   668.4   95.54  678.95  150.22  667.98
  825.26  664.61  833.12  661.85   859.6  652.79  884.26  660.39 1171.48  666.58
  1565.7  667.26 1852.98  662.52 2651.29   667.1 2728.36  677.68 2779.52  677.49
 2833.31  667.78 3012.95  665.49  3458.9  669.52 3522.46  677.17 3572.62  678.19
 3612.56   670.7 3712.67  668.48 4691.22  671.65 4802.05  681.65 4905.65  675.13
 5075.13  680.65 5213.19  672.41 5405.59   676.5 5474.73  700.34 5542.65  699.29
#Mann= 3 , 0 , 0
       0     .12       0  833.12    .045       0  884.26     .12       0
#XS Ineff= 1 ,-1
 2755.98 5573.72  701.34
Permanent Ineff=
       F
Bank Sta=833.12,884.26
XS Rating Curve= 0 ,0
Sediment Elevation=0
Exp/Cntr=0.5,0.3

Type RM Length L Ch R = 1 ,0.00    ,0,0,0
BEGIN DESCRIPTION:
0.08
END DESCRIPTION:
#Sta/Elev= 30
       0  683.67   65.65  678.64   90.89  667.99   98.55  680.53  112.01   667.3
  123.43   671.6  155.23  667.49  380.36  668.95  840.97  660.06  871.65  652.73
  896.56  659.87 1063.75  666.52  1715.6   661.4  2663.5  666.52 2717.54  677.39
 2764.75   677.2 2810.15  667.51 2931.55  665.11 3481.54  669.99 3588.29  677.79
 3654.92   668.4 4695.74  671.53 4825.64  681.73  4913.7  675.35 5058.82  680.86
 5145.19  672.47  5273.9  672.51 5413.67  676.92 5483.57  700.28 5557.24  699.55
#Mann= 3 , 0 , 0
       0     .12       0  840.97    .045       0  896.56     .12       0
#XS Ineff= 2 ,-1
 2721.89 5526.91  700.94 5526.91 5561.89680.9581
Permanent Ineff=
       F       F
Bank Sta=840.97,896.56
XS Rating Curve= 0 ,0
Exp/Cntr=0.3,0.1
Stream Node=RIVER-1         ,Reach-1         , 0 , 0 ,Upstream end
Stream Node=RIVER-1         ,Reach-1         , 0 , 1 ,Downstream end
LCMann Table=0

Chan Stop Cuts=-1
Use User Specified Reach Order=0
Composite Channel Slope=5

--- SpringCreek.g02 (geometry) ---

Geom Title=Duplicate Effective
Program Version=5.03

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
River Reach=RIVER-1         ,Reach-1

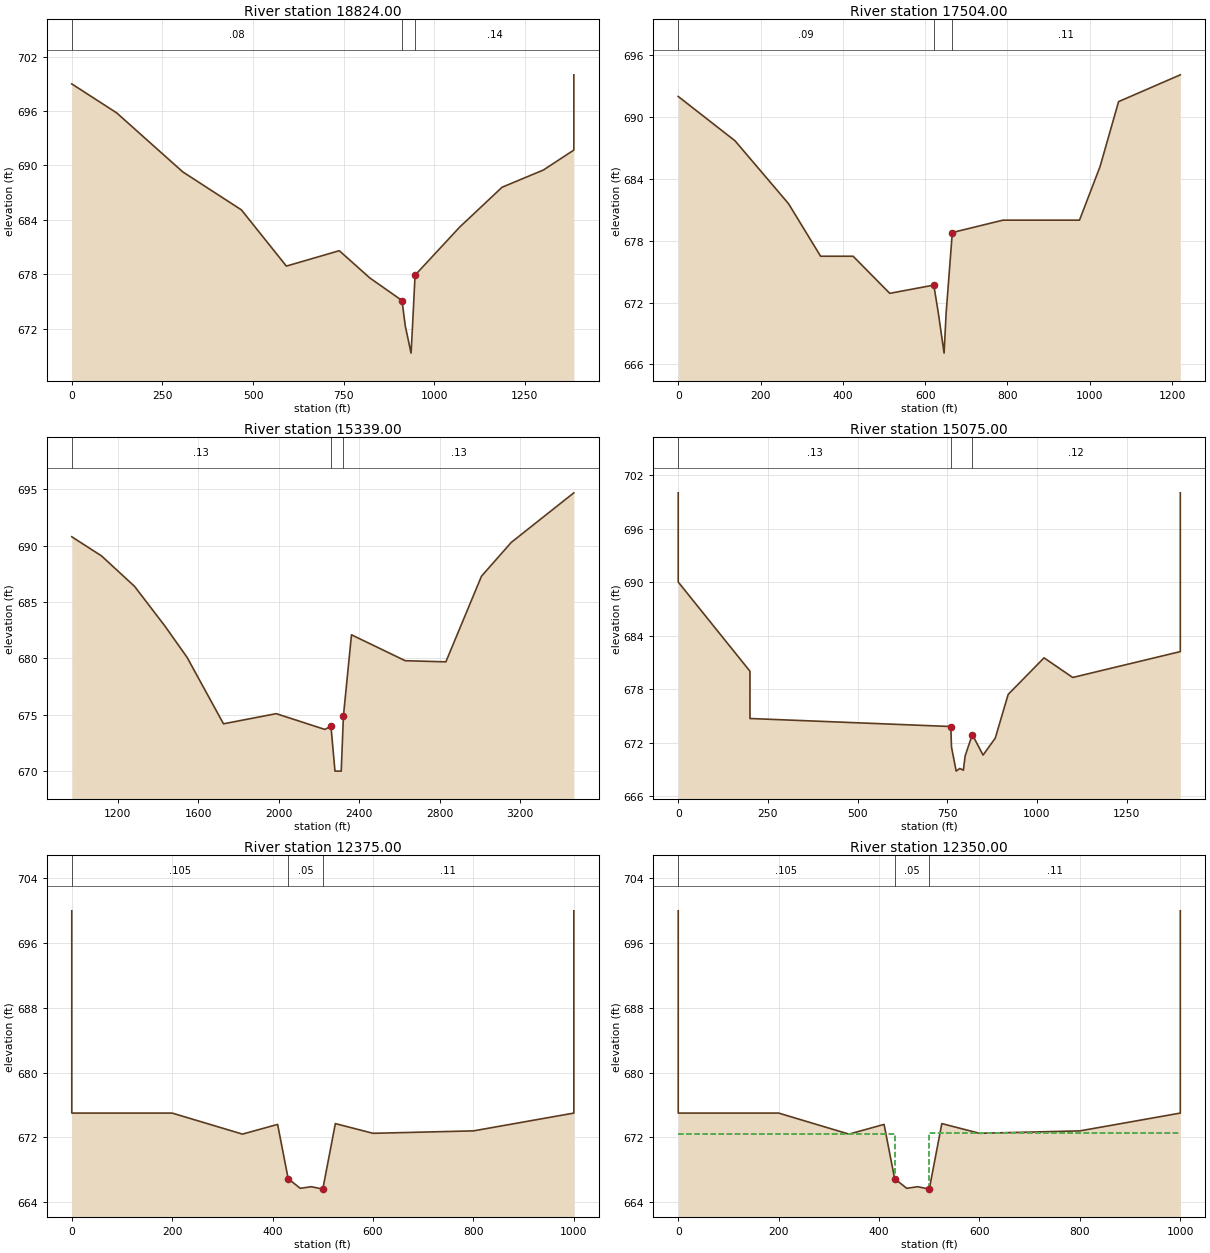
Type RM Length L Ch R = 1 ,18824.00,1320,1320,1320
BEGIN DESCRIPTION:
3.83
END DESCRIPTION:
#Sta/Elev= 17
       0     699     124   695.8     306   689.3     468   685.1     592   678.9
     738   680.6     822   677.6     911   675.1     920   672.3     936   669.3
     940   672.3     947   677.9    1070   683.2    1187   687.6    1301   689.5
    1385   691.7    1385     700
#Mann= 3 , 0 , 0
       0     .08       0     911    .043       0     947     .14       0
Bank Sta=911,947
XS Rating Curve= 0 ,0
Sediment Elevation=0
Exp/Cntr=0.5,0.1

Type RM Length L Ch R = 1 ,17504.00,2165,2165,2165
BEGIN DESCRIPTION:
3.56
END DESCRIPTION:
#Sta/Elev= 16
       0     692     138   687.7     268   681.6     346   676.5     425   676.5
     514   672.9     621   673.7     632     671     646   667.1     651     671
     666   678.8     789     680     975     680    1025   685.2    1070   691.5
    1220   694.1
#Mann= 3 , 0 , 0
       0     .09       0     621     .04       0     666     .11       0
Bank Sta=621,666
XS Rating Curve= 0 ,0
Sediment Elevation=0
Exp/Cntr=0.5,0.1

Type RM Length L Ch R = 1 ,15339.00,264,264,264
BEGIN DESCRIPTION:
3.15
END DESCRIPTION:
#Sta/Elev= 18
     972   690.8    1120   689.1    1284   686.4    1434   682.9    1545   680.1
    1726   674.2    1988   675.1    2230   673.7    2260     674    2280     670
    2311     670    2322   674.9    2362   682.1    2629   679.8    2831   679.7
    3008   687.3    3156   690.3    3467   694.7
#Mann= 3 , 0 , 0
     972     .13       0    2260    .045       0    2322     .13       0
Bank Sta=2260,2322
XS Rating Curve= 0 ,0
Sediment Elevation=0
Exp/Cntr=0.5,0.1

Type RM Length L Ch R = 1 ,15075.00,2700,2700,2700
BEGIN DESCRIPTION:
3.1 (F)
END DESCRIPTION:
#Sta/Elev= 18
       0     700       0     690     200     680     200   674.7     760   673.8
     762   671.5     775   668.8     785   669.1     795   668.9     800   670.5
     820   672.9     850   670.6     884   672.5     920   677.4    1020   681.5
    1100   679.3    1400   682.2    1400     700
#Mann= 3 , 0 , 0
       0     .13       0     760     .06       0     820     .12       0
Bank Sta=760,820
XS Rating Curve= 0 ,0
Sediment Elevation=0
Exp/Cntr=0.5,0.1

Type RM Length L Ch R = 1 ,12375.00,25,25,25
BEGIN DESCRIPTION:
2.57 (E)
END DESCRIPTION:
#Sta/Elev= 14
       0     700       0     675     200     675     340   672.4     410   673.6
     431   666.9     455   665.7     477   665.9     500   665.6     525   673.7
     600   672.5     800   672.8    1000     675    1000     700
#Mann= 3 , 0 , 0
       0    .105       0     431     .05       0     500     .11       0
Bank Sta=431,500
XS Rating Curve= 0 ,0
Sediment Elevation=0
Exp/Cntr=0.5,0.1

Type RM Length L Ch R = 1 ,12350.00,40,40,40
BEGIN DESCRIPTION:
2.57 (Springvale Road US)
END DESCRIPTION:
#Sta/Elev= 14
       0     700       0     675     200     675     340   672.4     410   673.6
     431   666.9     455   665.7     477   665.9     500   665.6     525   673.7
     600   672.5     800   672.8    1000     675    1000     700
#Mann= 3 , 0 , 0
       0    .105       0     431     .05       0     500     .11       0
#XS Ineff= 2 , 0
             431   672.4     500           672.5
Permanent Ineff=
       F       F
Bank Sta=431,500
XS Rating Curve= 0 ,0
Sediment Elevation=0
Exp/Cntr=0.5,0.1