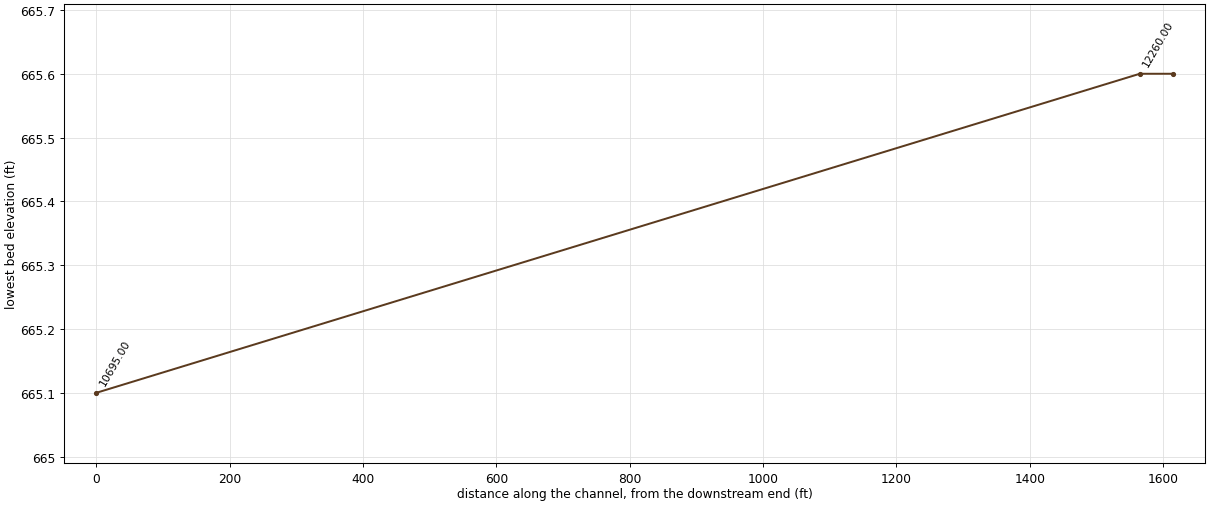
HEC-RAS study SpringCreek.prj: SpringCreek

--- SpringCreek.g02 (geometry) --- (continued)

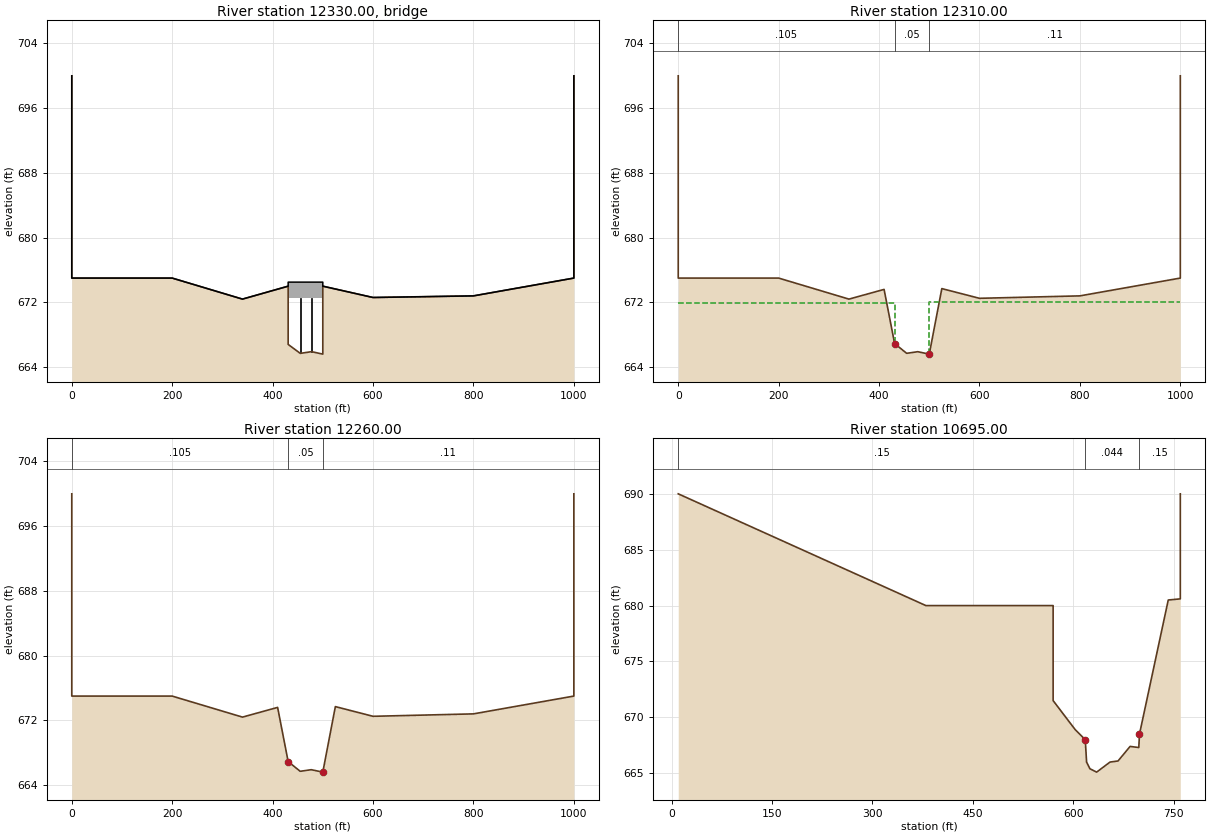
Type RM Length L Ch R = 3 ,12330.00,,,
BEGIN DESCRIPTION:
Springvale Road
END DESCRIPTION:
Bridge Culvert--1,0,-1,-1, 0
Deck Dist Width WeirC Skew NumUp NumDn MinLoCord MaxHiCord MaxSubmerge Is_Ogee
5,30,2.6,0, 12, 12, , , 0.98, 0, 0,0,,
       0       0     200     340     431     431     500     500     600     800
    1000    1000
     700     675     675   672.4     674   674.5   674.5     674   672.6   672.8
     675     700
       0       0       0       0       0   672.5   672.5       0       0       0
       0       0
       0       0     200     340     431     431     500     500     600     800
    1000    1000
     700     675     675   672.4     674   674.5   674.5     674   672.6   672.8
     675     700
       0       0       0       0       0   672.5   672.5       0       0       0
       0       0
Pier Skew, UpSta & Num, DnSta & Num=  ,455.5, 2 ,455.5, 2 , 0 , 0 , 0 ,,
       1       1
   665.7   672.5
       1       1
   665.7   672.5
Pier Skew, UpSta & Num, DnSta & Num=  ,477.5, 2 ,477.5, 2 , 0 , 0 , 0 ,,
       1       1
   665.9   672.5
       1       1
   665.9   672.5
BR Coef=-1 , 0 , 0 ,, 0 ,,,0.8,0,2,1,
WSPro=,,,, 1 ,,,, 0 ,,,, 0 ,,,,-1 ,-1 ,-1 , 0 , 0 , 0 , 0 , 0
BR U #Sta/Elev= 16
       0     700       0     675     200     675     340   672.4     431     674
     431   666.8     455   665.7     456   665.7     477   665.9     478   665.9
     500   665.6     500     674     600   672.6     800   672.8    1000     675
    1000     700
BR U #Mann= 3
       0    .105     431     .05     477     .11
BR D #Sta/Elev= 16
       0     700       0     675     200     675     340   672.4     431     674
     431   666.8     455   665.7     456   665.7     477   665.9     478   665.9
     500   665.6     500     674     600   672.6     800   672.8    1000     675
    1000     700
BR D #Mann= 3
       0    .105     431     .05     477     .11
BC Design=,, 0 ,, 0 ,,,,,,
BC Use User HTab Curves=0
BC User HTab FreeFlow(D)= 0

Type RM Length L Ch R = 1 ,12310.00,50,50,50
BEGIN DESCRIPTION:
2.57 (Springvale Road DS)
END DESCRIPTION:
#Sta/Elev= 14
       0     700       0     675     200     675     340   672.4     410   673.6
     431   666.9     455   665.7     477   665.9     500   665.6     525   673.7
     600   672.5     800   672.8    1000     675    1000     700
#Mann= 3 , 0 , 0
       0    .105       0     431     .05       0     500     .11       0
#XS Ineff= 2 , 0
       0     431   671.9     500       0     672
Permanent Ineff=
       F       F
Bank Sta=431,500
XS Rating Curve= 0 ,0
Sediment Elevation=0
Exp/Cntr=0.5,0.1

Type RM Length L Ch R = 1 ,12260.00,1565,1565,1565
BEGIN DESCRIPTION:
2.57
END DESCRIPTION:
#Sta/Elev= 14
       0     700       0     675     200     675     340   672.4     410   673.6
     431   666.9     455   665.7     477   665.9     500   665.6     525   673.7
     600   672.5     800   672.8    1000     675    1000     700
#Mann= 3 , 0 , 0
       0    .105       0     431     .05       0     500     .11       0
Bank Sta=431,500
XS Rating Curve= 0 ,0
Sediment Elevation=0
Exp/Cntr=0.5,0.1

Type RM Length L Ch R = 1 ,10695.00,30,30,30
BEGIN DESCRIPTION:
2.26 (D)
END DESCRIPTION:
#Sta/Elev= 17
      10     690     380     680     570     680     570   671.5     603   668.9
     618     668     620     666     625   665.4     635   665.1     655     666
     667   666.1     685   667.4     698   667.3     699   668.5     742   680.5
     760   680.6     760     690
#Mann= 3 , 0 , 0
      10     .15       0     618    .044       0     699     .15       0
Bank Sta=618,699
XS Rating Curve= 0 ,0
Sediment Elevation=0
Exp/Cntr=0.5,0.1