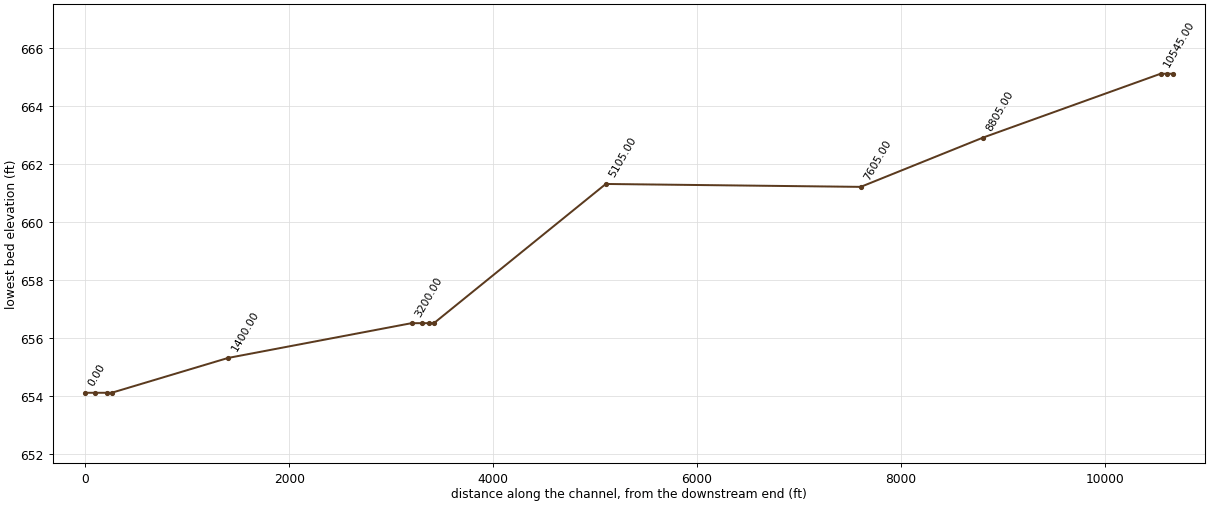
HEC-RAS study SpringCreek.prj: SpringCreek

--- SpringCreek.g02 (geometry) --- (continued)

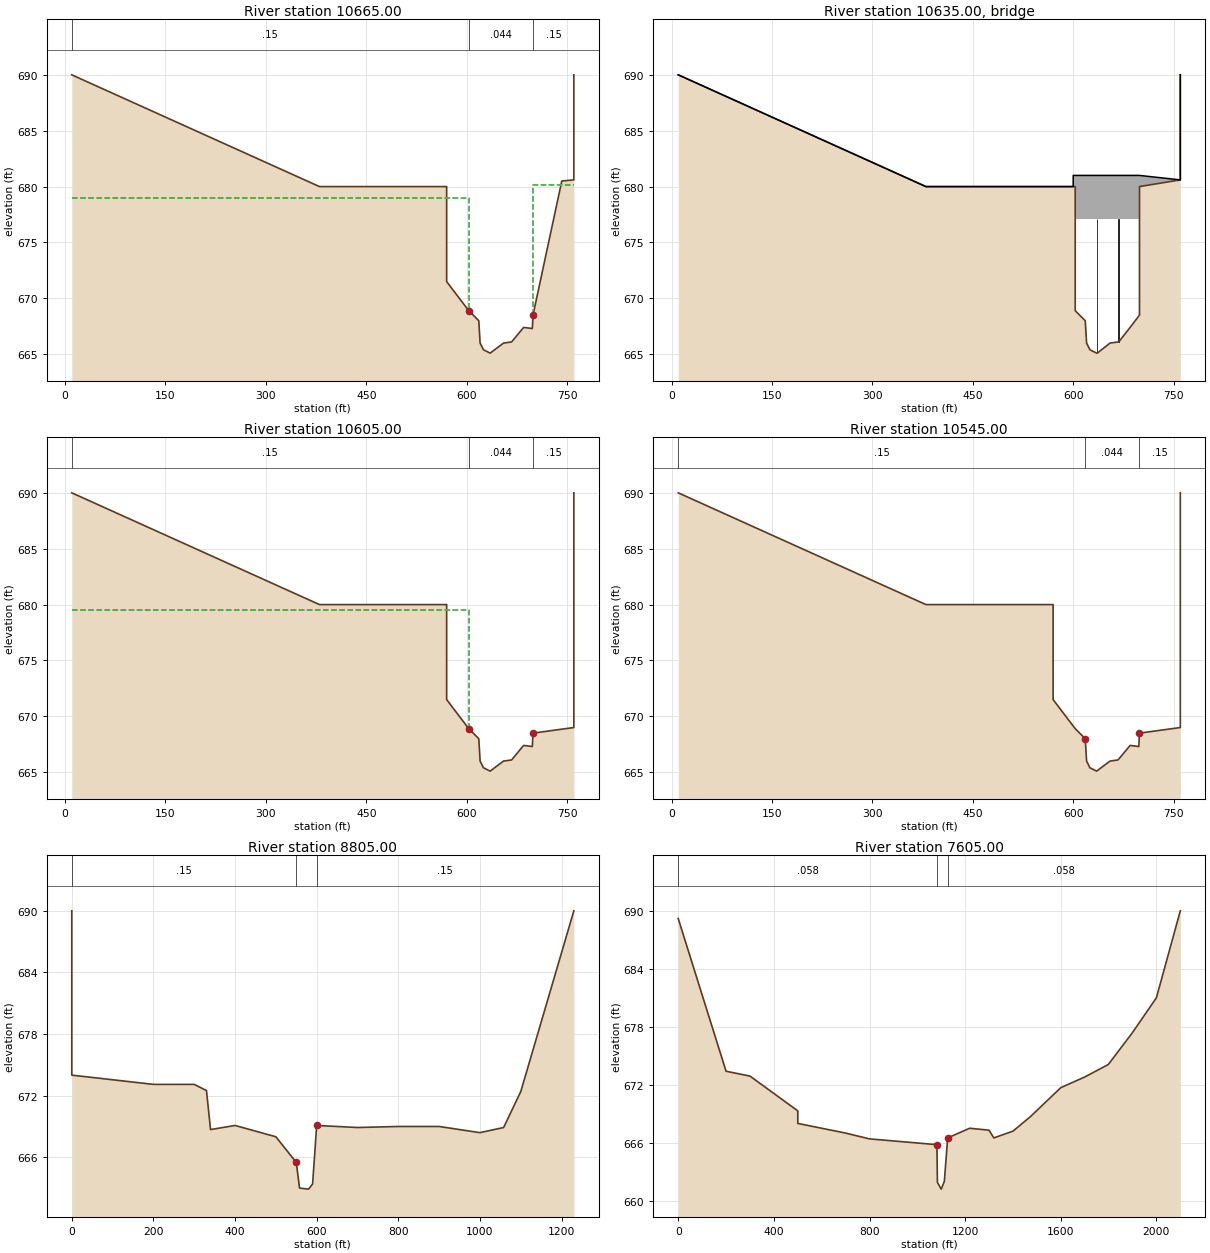
Type RM Length L Ch R = 1 ,10665.00,60,60,60
BEGIN DESCRIPTION:
2.26 (Ringgold Road US)
END DESCRIPTION:
#Sta/Elev= 17
      10     690     380     680     570     680     570   671.5     603   668.9
     618     668     620     666     625   665.4     635   665.1     655     666
     667   666.1     685   667.4     698   667.3     699   668.5     742   680.5
     760   680.6     760     690
#Mann= 3 , 0 , 0
      10     .15       0     603    .044       0     699     .15       0
#XS Ineff= 2 , 0
             603     679     699           680.1
Permanent Ineff=
       F       F
Bank Sta=603,699
XS Rating Curve= 0 ,0
Sediment Elevation=0
Exp/Cntr=0.5,0.1

Type RM Length L Ch R = 3 ,10635.00,,,
BEGIN DESCRIPTION:
Ringgold Road
END DESCRIPTION:
Bridge Culvert--1,0,-1,-1, 0
Deck Dist Width WeirC Skew NumUp NumDn MinLoCord MaxHiCord MaxSubmerge Is_Ogee
5,50,2.6,0, 11, 11, , , 0.98, 0, 0,0,,
      10     380     500     600     600     603     603     699     699     760
     760
     690     680     680     680     681     681     681     681     681   680.6
     690
       0       0       0       0       0       0   677.1   677.1       0       0
       0
      10     380     500     600     600     603     603     699     699     760
     760
     690     680     680     680     681     681     681     681     681   680.6
     690
       0       0       0       0       0       0   677.1   677.1       0       0
       0
Pier Skew, UpSta & Num, DnSta & Num=  ,635.5, 2 ,635.5, 2 , 0 , 0 , 0 ,,
       1       1
   665.1   677.1
       1       1
   665.1   677.1
Pier Skew, UpSta & Num, DnSta & Num=  ,667.5, 2 ,667.5, 2 , 0 , 0 , 0 ,,
       1       1
   666.1   677.1
       1       1
   666.1   677.1
BR Coef=-1 , 0 , 0 ,, 0 ,,,0.8,0,2,1,
WSPro=,,,, 1 ,,,, 0 ,,,, 0 ,,,,-1 ,-1 ,-1 , 0 , 0 , 0 , 0 , 0
BR U #Sta/Elev= 19
      10     690     380     680     500     680     600     680     603     680
     603   668.9     618     668     620     666     625   665.4     635   665.1
     636   665.1     655     666     667   666.1     668   666.1     685   667.4
     699   668.5     699     680     760   680.6     760     690
BR U #Mann= 3
      10     .15     603    .044     668     .15
BR D #Sta/Elev= 19
      10     690     380     680     500     680     600     680     603     680
     603   668.9     618     668     620     666     625   665.4     635   665.1
     636   665.1     655     666     667   666.1     668   666.1     685   667.4
     699   668.5     699     680     760   680.6     760     690
BR D #Mann= 3
      10     .15     603    .044     668     .15
BC Design=,, 0 ,, 0 ,,,,,,
BC Use User HTab Curves=0
BC User HTab FreeFlow(D)= 0

Type RM Length L Ch R = 1 ,10605.00,60,60,60
BEGIN DESCRIPTION:
2.26 (Ringgold Road DS)
END DESCRIPTION:
#Sta/Elev= 16
      10     690     380     680     570     680     570   671.5     603   668.9
     618     668     620     666     625   665.4     635   665.1     655     666
     667   666.1     685   667.4     698   667.3     699   668.5     760     669
     760     690
#Mann= 3 , 0 , 0
      10     .15       0     603    .044       0     699     .15       0
#XS Ineff= 2 , 0
       0     603   679.5     699       0   780.5
Permanent Ineff=
       F       F
Bank Sta=603,699
XS Rating Curve= 0 ,0
Sediment Elevation=0
Exp/Cntr=0.5,0.1

Type RM Length L Ch R = 1 ,10545.00,1740,1740,1740
BEGIN DESCRIPTION:
2.26
END DESCRIPTION:
#Sta/Elev= 16
      10     690     380     680     570     680     570   671.5     603   668.9
     618     668     620     666     625   665.4     635   665.1     655     666
     667   666.1     685   667.4     698   667.3     699   668.5     760     669
     760     690
#Mann= 3 , 0 , 0
      10     .15       0     618    .044       0     699     .15       0
Bank Sta=618,699
XS Rating Curve= 0 ,0
Sediment Elevation=0
Exp/Cntr=0.5,0.1

Type RM Length L Ch R = 1 ,8805.00 ,1200,1200,1200
BEGIN DESCRIPTION:
1.92
END DESCRIPTION:
#Sta/Elev= 20
       0     690       0     674     200   673.1     300   673.1     330   672.5
     340   668.7     400   669.1     500     668     550   665.5     558     663
     580   662.9     590   663.4     600   669.1     700   668.9     800     669
     900     669    1000   668.4    1058   668.9    1100   672.4    1230     690
#Mann= 3 , 0 , 0
       0     .15       0     550    .032       0     600     .15       0
Bank Sta=550,600
XS Rating Curve= 0 ,0
Sediment Elevation=0
Exp/Cntr=0.5,0.1

Type RM Length L Ch R = 1 ,7605.00 ,2500,2500,2500
BEGIN DESCRIPTION:
1.6
END DESCRIPTION:
#Sta/Elev= 24
       0   689.2     200   673.4     300   672.9     400   671.1     500   669.3
     500     668     700     667     800   666.4    1082   665.8    1084   661.9
    1100   661.2    1113     662    1127   666.5    1219   667.5    1300   667.3
    1320   666.5    1400   667.2    1473   668.7    1600   671.7    1700   672.8
    1799   674.1    1900   677.4    2000     681    2100     690
#Mann= 3 , 0 , 0
       0    .058       0    1082    .019       0    1127    .058       0
Bank Sta=1082,1127
XS Rating Curve= 0 ,0
Sediment Elevation=0
Exp/Cntr=0.5,0.1

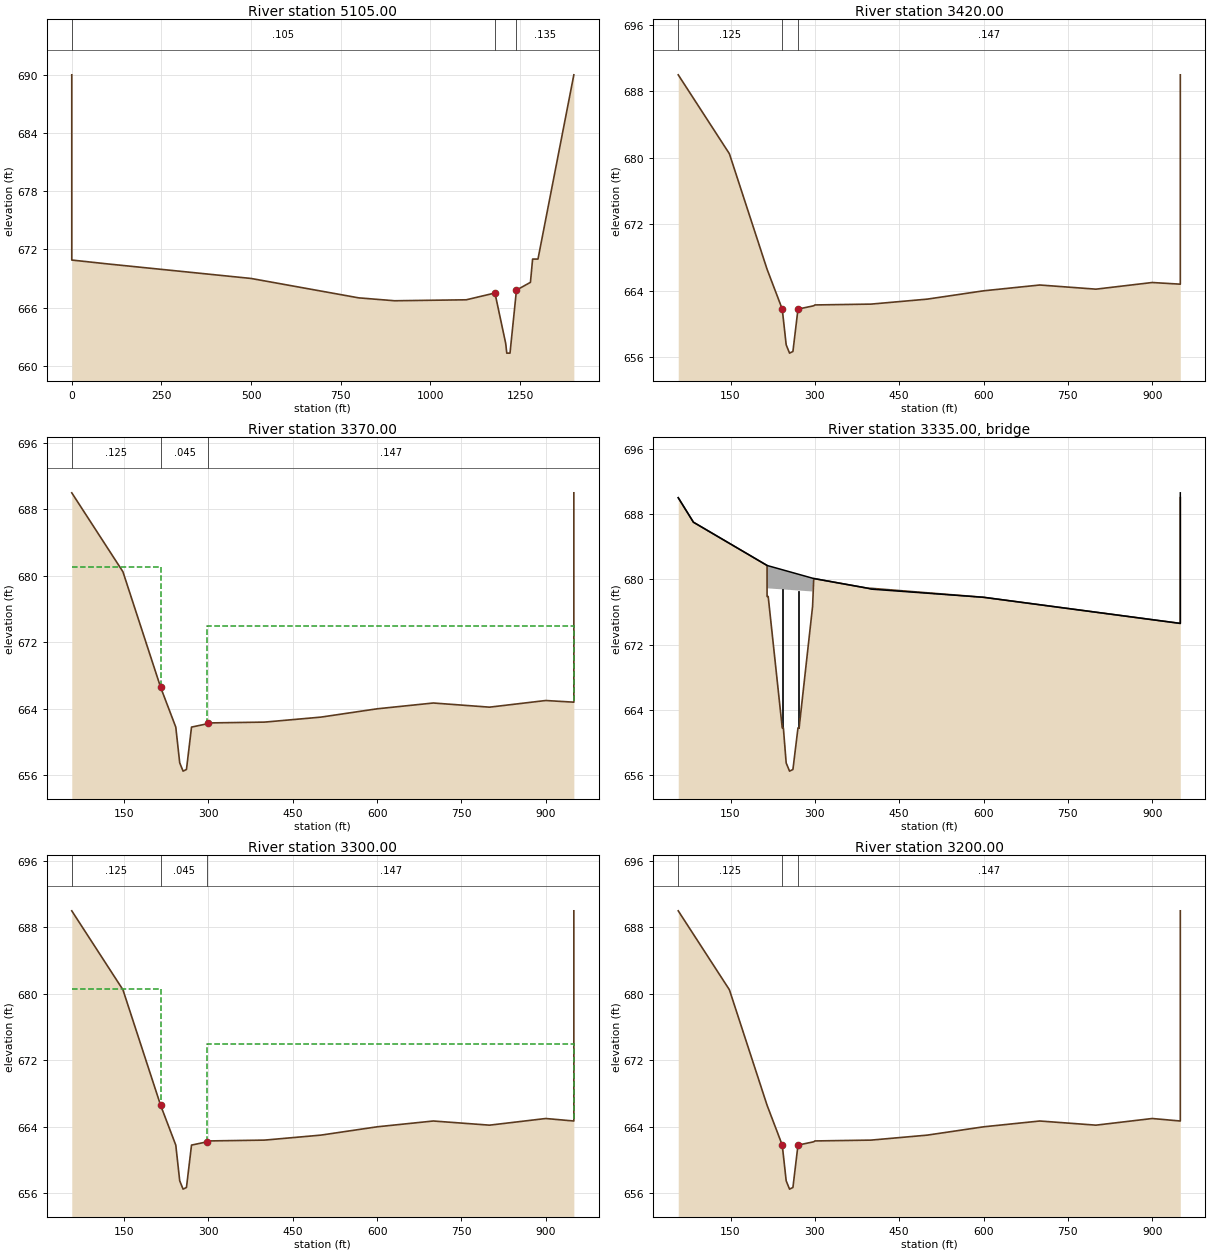
Type RM Length L Ch R = 1 ,5105.00 ,1685,1685,1685
BEGIN DESCRIPTION:
1.07
END DESCRIPTION:
#Sta/Elev= 16
       0     690       0   670.9     100   670.5     500     669     800     667
     900   666.7    1100   666.8    1180   667.5    1210   662.3    1213   661.3
    1222   661.3    1240   667.8    1279   668.6    1285     671    1300     671
    1400     690
#Mann= 3 , 0 , 0
       0    .105       0    1180    .021       0    1240    .135       0
Bank Sta=1180,1240
XS Rating Curve= 0 ,0
Sediment Elevation=0
Exp/Cntr=0.5,0.1

Type RM Length L Ch R = 1 ,3420.00 ,50,50,50
BEGIN DESCRIPTION:
0.7 (C)
END DESCRIPTION:
#Sta/Elev= 18
      57     690     148   680.5     215   666.6     242   661.8     249   657.5
     255   656.5     261   656.7     270   661.8     298   662.2     300   662.3
     400   662.4     500     663     600     664     700   664.7     800   664.2
     900     665     950   664.8     950     690
#Mann= 3 , 0 , 0
      57    .125       0     242    .045       0     270    .147       0
Bank Sta=242,270
XS Rating Curve= 0 ,0
Sediment Elevation=0
Exp/Cntr=0.5,0.1

Type RM Length L Ch R = 1 ,3370.00 ,70,70,70
BEGIN DESCRIPTION:
0.7 (Spring Creek Road US)
END DESCRIPTION:
#Sta/Elev= 18
      57     690     148   680.5     215   666.6     242   661.8     249   657.5
     255   656.5     261   656.7     270   661.8     298   662.2     300   662.3
     400   662.4     500     663     600     664     700   664.7     800   664.2
     900     665     950   664.8     950     690
#Mann= 3 , 0 , 0
      57    .125       0     215    .045       0     300    .147       0
#XS Ineff= 2 , 0
       0     215   681.1     298       0     674
Permanent Ineff=
       F       F
Bank Sta=215,300
XS Rating Curve= 0 ,0
Sediment Elevation=0
Exp/Cntr=0.5,0.1

Type RM Length L Ch R = 3 ,3335.00 ,,,
BEGIN DESCRIPTION:
Spring Creek Road
END DESCRIPTION:
Bridge Culvert--1,0,-1,-1, 0
Deck Dist Width WeirC Skew NumUp NumDn MinLoCord MaxHiCord MaxSubmerge Is_Ogee
5,60,2.6,0, 11, 11, , , 0.98, 0, 0,0,,
      57      84     215     215     298     298     395     400     600     950
     950
     690     687   681.7   681.7   680.1   680.1   678.9   678.8   677.8   674.6
   690.6
       0       0       0   678.9   678.5       0       0       0       0       0
       0
      57      84     215     215     298     298     395     400     600     950
     950
     690     687   681.7   681.7   680.1   680.1   678.9   678.8   677.8   674.6
   690.6
       0       0       0   678.9   678.5       0       0       0       0       0
       0
Pier Skew, UpSta & Num, DnSta & Num=  ,243, 2 ,243, 2 , 0 , 0 , 0 ,,
       2       2
   661.8   678.8
       2       2
   661.8   678.8
Pier Skew, UpSta & Num, DnSta & Num=  ,271, 2 ,271, 2 , 0 , 0 , 0 ,,
       2       2
   661.8   678.7
       2       2
   661.8   678.7
BR Coef=-1 , 0 , 0 ,, 0 ,,,0.8,0,2,1,
WSPro=,,,, 1 ,,,, 0 ,,,, 0 ,,,,-1 ,-1 ,-1 , 0 , 0 , 0 , 0 , 0
BR U #Sta/Elev= 19
      57     690      84     687     215   681.7     215   677.9     217   677.9
     242   661.8     244   661.8     249   657.5     255   656.5     261   656.7
     270   661.8     272   661.8     296   676.7     298   680.1     395   678.9
     400   678.9     600   677.8     950   674.6     950     690
BR U #Mann= 3
      57    .125     215    .045     261    .147
BR U Banks=,298
BR D #Sta/Elev= 19
      57     690      84     687     215   681.7     215   677.9     217   677.9
     242   661.8     244   661.8     249   657.5     255   656.5     261   656.7
     270   661.8     272   661.8     296   676.7     298   680.1     395   678.9
     400   678.9     600   677.8     950   674.6     950     690
BR D #Mann= 3
      57    .125     215    .045     255    .147
BC Design=,, 0 ,, 0 ,,,,,,
BC Use User HTab Curves=0
BC User HTab FreeFlow(D)= 0

Type RM Length L Ch R = 1 ,3300.00 ,100,100,100
BEGIN DESCRIPTION:
0.7 (Spring Creek Road DS)
END DESCRIPTION:
#Sta/Elev= 18
      57     690     148   680.5     215   666.6     242   661.8     249   657.5
     255   656.5     261   656.7     270   661.8     298   662.2     300   662.3
     400   662.4     500     663     600     664     700   664.7     800   664.2
     900     665     950   664.7     950     690
#Mann= 3 , 0 , 0
      57    .125       0     215    .045       0     298    .147       0
#XS Ineff= 2 , 0
       0     215   680.6     298       0     674
Permanent Ineff=
       F       F
Bank Sta=215,298
XS Rating Curve= 0 ,0
Sediment Elevation=0
Exp/Cntr=0.5,0.1

Type RM Length L Ch R = 1 ,3200.00 ,1800,1800,1800
BEGIN DESCRIPTION:
0.7
END DESCRIPTION:
#Sta/Elev= 18
      57     690     148   680.5     215   666.6     242   661.8     249   657.5
     255   656.5     261   656.7     270   661.8     298   662.2     300   662.3
     400   662.4     500     663     600     664     700   664.7     800   664.2
     900     665     950   664.7     950     690
#Mann= 3 , 0 , 0
      57    .125       0     242    .045       0     270    .147       0
Bank Sta=242,270
XS Rating Curve= 0 ,0
Sediment Elevation=0
Exp/Cntr=0.5,0.1

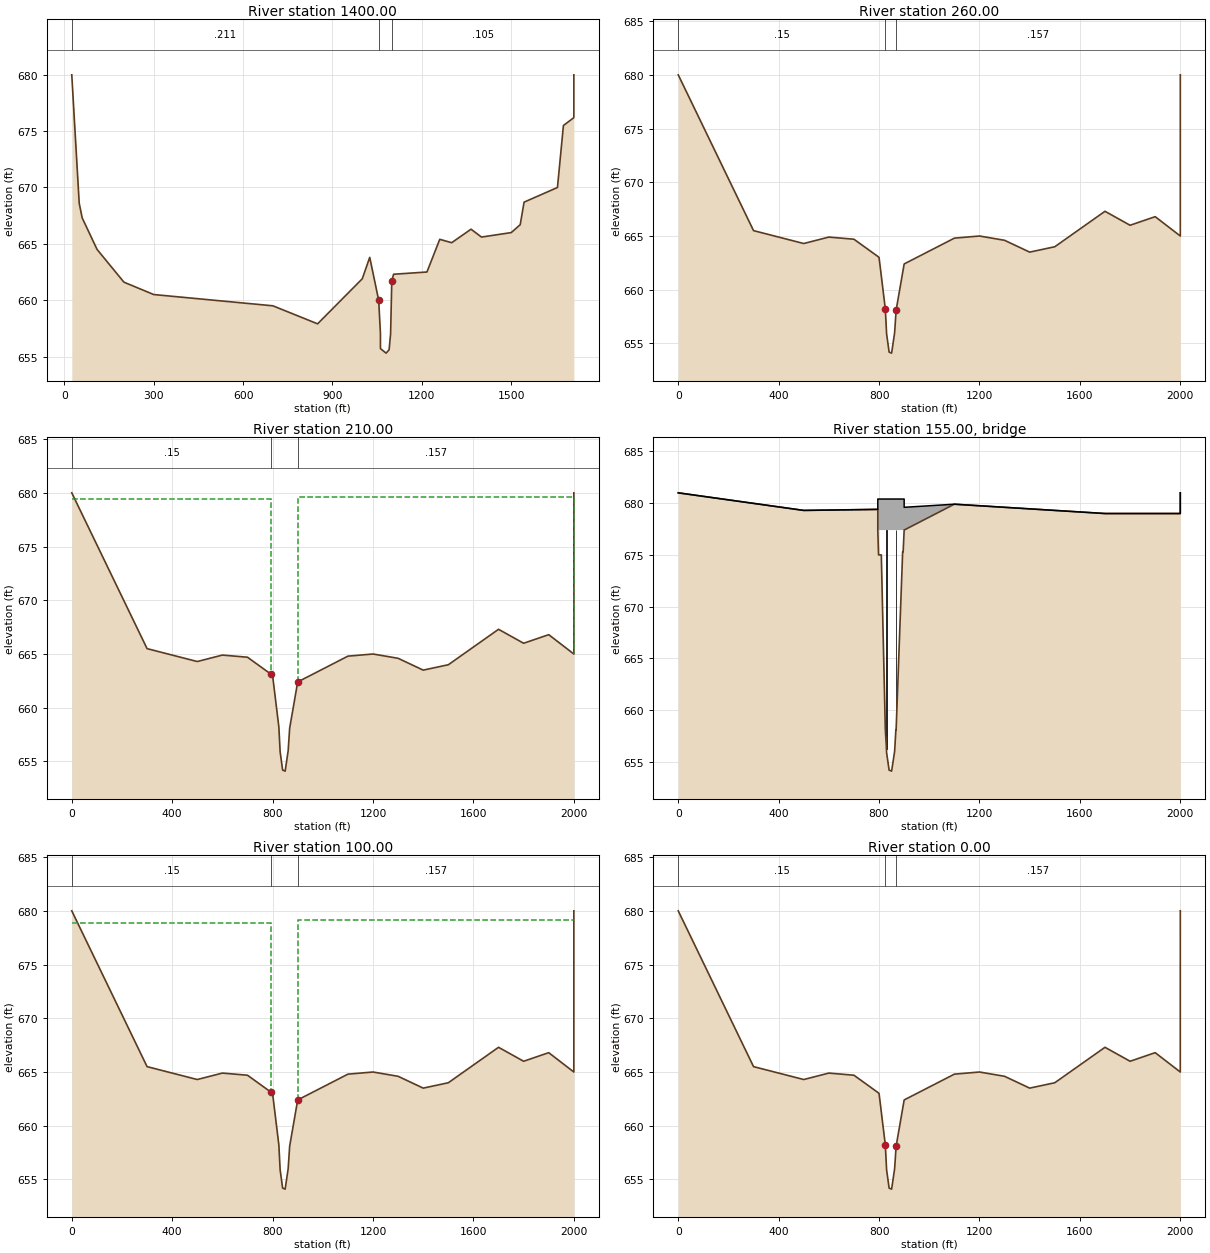
Type RM Length L Ch R = 1 ,1400.00 ,1140,1140,1140
BEGIN DESCRIPTION:
0.32 (B)
END DESCRIPTION:
#Sta/Elev= 30
      25     680      50   668.6      60   667.3     110   664.5     200   661.6
     300   660.5     700   659.5     850   657.9    1000   661.9    1025   663.8
    1055     660    1061     657    1061   655.7    1080   655.3    1090   655.6
    1095     657    1099   661.7    1105   662.3    1217   662.5    1260   665.4
    1300   665.1    1365   666.3    1400   665.6    1500     666    1530   666.7
    1543   668.7    1655     670    1675   675.5    1710   676.2    1710     680
#Mann= 3 , 0 , 0
      25    .211       0    1055     .07       0    1099    .105       0
Bank Sta=1055,1099
XS Rating Curve= 0 ,0
Sediment Elevation=0
Exp/Cntr=0.5,0.1

Type RM Length L Ch R = 1 ,260.00  ,50,50,50
BEGIN DESCRIPTION:
0.08 (A)
END DESCRIPTION:
#Sta/Elev= 24
       0     680     300   665.5     500   664.3     600   664.9     700   664.7
     795   663.1     800     663     825   658.2     830   655.9     840   654.2
     850   654.1     862     656     868   658.1     900   662.4    1100   664.8
    1200     665    1300   664.6    1400   663.5    1500     664    1700   667.3
    1800     666    1900   666.8    2000     665    2000     680
#Mann= 3 , 0 , 0
       0     .15       0     825    .065       0     868    .157       0
Bank Sta=825,868
XS Rating Curve= 0 ,0
Sediment Elevation=0
Exp/Cntr=0.5,0.1

Type RM Length L Ch R = 1 ,210.00  ,110,110,110
BEGIN DESCRIPTION:
0.08 (I75 US)
END DESCRIPTION:
#Sta/Elev= 24
       0     680     300   665.5     500   664.3     600   664.9     700   664.7
     795   663.1     800     663     825   658.2     830   655.9     840   654.2
     850   654.1     862     656     868   658.1     900   662.4    1100   664.8
    1200     665    1300   664.6    1400   663.5    1500     664    1700   667.3
    1800     666    1900   666.8    2000     665    2000     680
#Mann= 3 , 0 , 0
       0     .15       0     795     .04       0     900    .157       0
#XS Ineff= 2 , 0
             795   679.4     900           679.6
Permanent Ineff=
       F       F
Bank Sta=795,900
XS Rating Curve= 0 ,0
Sediment Elevation=0
Exp/Cntr=0.5,0.1

Type RM Length L Ch R = 3 ,155.00  ,,,
BEGIN DESCRIPTION:
I75
END DESCRIPTION:
Bridge Culvert--1,0,-1,-1, 0
Deck Dist Width WeirC Skew NumUp NumDn MinLoCord MaxHiCord MaxSubmerge Is_Ogee
5,100,2.6,0, 11, 11, , , 0.98, 0, 0,0,,
       0     500     795     795     900     900    1100    1300    1700    2000
  2000.1
     681   679.3   679.4   680.4   680.4   679.6   679.9   679.6     679     679
     681
       0       0       0   677.4   677.4       0       0       0       0       0
       0
       0     500     795     795     900     900    1100    1300    1700    2000
  2000.1
     681   679.3   679.4   680.4   680.4   679.6   679.9   679.6     679     679
     681
       0       0       0   677.4   677.4       0       0       0       0       0
       0
Pier Skew, UpSta & Num, DnSta & Num=  ,829.5, 2 ,829.5, 2 , 0 , 0 , 0 ,,
       1       1
   656.5   677.5
       1       1
   656.5   677.5
Pier Skew, UpSta & Num, DnSta & Num=  ,867.5, 2 ,867.5, 2 , 0 , 0 , 0 ,,
       1       1
   658.1   677.5
       1       1
   658.1   677.5
BR Coef=-1 , 0 , 0 ,, 0 ,,,0.8,0,2,1,
WSPro=,,,, 1 ,,,, 0 ,,,, 0 ,,,,-1 ,-1 ,-1 , 0 , 0 , 0 , 0 , 0
BR U #Sta/Elev= 22
       0     681     500   679.3     795   679.4     795   677.4     798     675
     809     675     825   658.1     829   656.5     830   655.9     840   654.2
     850   654.1     862     656     867   658.1     868   658.1     894   675.3
     896   675.3     900   677.4    1100   679.9    1300   679.6    1700     679
    2000     679    2000     681
BR U #Mann= 3
       0     .15     809     .04     868    .157
BR D #Sta/Elev= 22
       0     681     500   679.3     795   679.4     795   677.4     798     675
     809     675     825   658.1     829   656.5     830   655.9     840   654.2
     850   654.1     862     656     867   658.1     868   658.1     894   675.3
     896   675.3     900   677.4    1100   679.9    1300   679.6    1700     679
    2000     679    2000     681
BR D #Mann= 3
       0     .15     809     .04     868    .157
BC Design=,, 0 ,, 0 ,,,,,,
BC Use User HTab Curves=0
BC User HTab FreeFlow(D)= 0

Type RM Length L Ch R = 1 ,100.00  ,100,100,100
BEGIN DESCRIPTION:
0.08 (I75 DS)
END DESCRIPTION:
#Sta/Elev= 24
       0     680     300   665.5     500   664.3     600   664.9     700   664.7
     795   663.1     800     663     825   658.2     830   655.9     840   654.2
     850   654.1     862     656     868   658.1     900   662.4    1100   664.8
    1200     665    1300   664.6    1400   663.5    1500     664    1700   667.3
    1800     666    1900   666.8  1999.9     665    2000     680
#Mann= 3 , 0 , 0
       0     .15       0     795     .04       0     900    .157       0
#XS Ineff= 2 , 0
       0     795   678.9     900       0   679.1
Permanent Ineff=
       F       F
Bank Sta=795,900
XS Rating Curve= 0 ,0
Sediment Elevation=0
Exp/Cntr=0.5,0.1

Type RM Length L Ch R = 1 ,0.00    ,0,0,0
BEGIN DESCRIPTION:
0.08
END DESCRIPTION:
#Sta/Elev= 24
       0     680     300   665.5     500   664.3     600   664.9     700   664.7
     795   663.1     800     663     825   658.2     830   655.9     840   654.2
     850   654.1     862     656     868   658.1     900   662.4    1100   664.8
    1200     665    1300   664.6    1400   663.5    1500     664    1700   667.3
    1800     666    1900   666.8  1999.9     665    2000     680
#Mann= 3 , 0 , 0
       0     .15       0     825    .065       0     868    .157       0
Bank Sta=825,868
XS Rating Curve= 0 ,0
Exp/Cntr=0.5,0.1
Stream Node=RIVER-1         ,Reach-1         , 0 , 0 ,Upstream end
Stream Node=RIVER-1         ,Reach-1         , 0 , 1 ,Downstream end
LCMann Table=0

--- SpringCreek.g05 (geometry) ---

Geom Title=Existing
Program Version=5.03

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
River Reach=RIVER-1         ,Reach-1

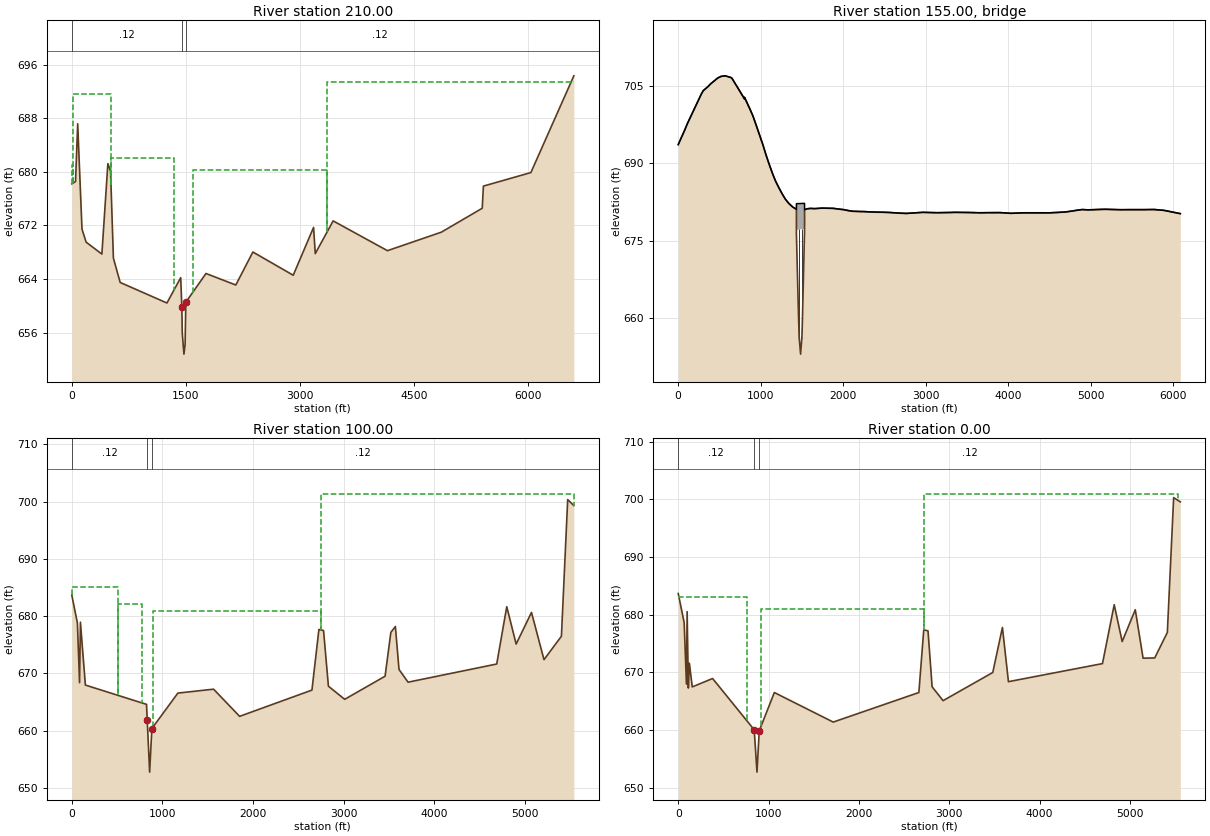
Type RM Length L Ch R = 1 ,210.00  ,499.99,491.72,481.81
BEGIN DESCRIPTION:
0.08 (I75 US)
END DESCRIPTION:
#Sta/Elev= 30
       0  678.22   49.39  678.55   77.76   687.2  134.43  671.45  188.51  669.51
  395.81  667.72  474.67  681.24   509.7  680.12  547.36  667.11  636.41  663.48
 1251.07  660.41 1432.08   664.2 1447.17  659.79 1452.55  655.91 1474.44  652.77
  1489.9  654.21 1499.13  660.52  1764.3  664.82 2156.39   663.1 2380.94  668.03
 2911.17  664.56 3178.76  671.71  3200.9  667.79 3435.96  672.68 4150.11  668.23
 4858.96     671 5395.72  674.57  5411.1  677.88 6035.03   679.9 6600.01  694.36
#Mann= 3 , 0 , 0
       0     .12       0 1447.17    .045       0 1499.13     .12       0
#XS Ineff= 5 ,-1
       0    11.9   681.1    11.9  515.87  691.65  515.87 1346.79682.0934
 1587.18 3357.66  680.26 3357.66 6597.64  693.38
Permanent Ineff=
       F       F       F       F       F
Bank Sta=1447.17,1499.13
XS Rating Curve= 0 ,0
Sediment Elevation=0
Exp/Cntr=0.5,0.3

Type RM Length L Ch R = 3 ,155.00  ,,,
BEGIN DESCRIPTION:
I75
END DESCRIPTION:
Bridge Culvert--1,0,-1,-1, 0
Deck Dist Width WeirC Skew NumUp NumDn MinLoCord MaxHiCord MaxSubmerge Is_Ogee
80,303,2.6,0, 55, 45, , , 0.98, 0, 0,0,,
     .83   80.33  112.23  280.76  303.85  359.11  398.99   478.8  518.82  570.87
   645.4  655.55  803.14  803.16  868.66  907.58 1028.88 1058.54 1098.55 1138.49
 1178.05 1218.21  1258.3 1298.23 1338.22  1388.2 1432.98 1432.98 1531.41 1531.41
 1562.42 1601.51 1654.93 1743.63  1879.4 1999.37    2114 2554.67 2764.39  2964.4
 3134.12 3354.25 3644.29 3899.42 4029.28 4189.27 4487.43 4691.73 4897.23 4967.25
 5177.32 5359.67 5767.55 5887.69 6084.55
  693.62  696.47  697.71  703.42  704.07  704.82  705.47  706.51  706.83  706.94
  706.57  706.37  702.49  702.78  700.54  699.11  693.49  691.93  690.01  688.23
  686.64  685.34  684.14  683.08  682.28  681.54   681.1  682.19  682.25  681.01
   681.2  681.27  681.23  681.33  681.28  681.05  680.72  680.49   680.3  680.51
  680.44  680.51  680.43  680.46  680.32  680.42  680.41  680.58  681.05  680.99
   681.1  681.02  681.06  680.89  680.26
       0       0       0       0       0       0       0       0       0       0
       0       0       0       0       0       0       0       0       0       0
       0       0       0       0       0       0       0  677.13  677.32       0
       0       0       0       0       0       0       0       0       0       0
       0       0       0       0       0       0       0       0       0       0
       0       0       0       0       0
     5.4   15.55  163.14  163.16  228.66  267.58  388.88  418.54  458.55  498.49
  538.05  578.21   618.3  658.23  698.22   748.2  792.98  792.98  891.41  891.41
  922.42  961.51 1014.93 1103.63  1239.4 1359.37    1474 1914.67 2124.39  2324.4
 2494.12 2714.25 3004.29 3259.42 3389.28 3549.27 3847.43 4051.73 4257.23 4327.25
 4537.32 4719.67 5127.55 5247.69 5444.55
  706.57  706.37  702.49  702.78  700.54  699.11  693.49  691.93  690.01  688.23
  686.64  685.34  684.14  683.08  682.28  681.54   681.1  682.19  682.25  681.01
   681.2  681.27  681.23  681.33  681.28  681.05  680.72  680.49   680.3  680.51
  680.44  680.51  680.43  680.46  680.32  680.42  680.41  680.58  681.05  680.99
   681.1  681.02  681.06  680.89  680.26
       0       0       0       0       0       0       0       0       0       0
       0       0       0       0       0       0       0  677.13  677.32       0
       0       0       0       0       0       0       0       0       0       0
       0       0       0       0       0       0       0       0       0       0
       0       0       0       0       0
Pier Skew, UpSta & Num, DnSta & Num=  ,1466.71, 2 ,826.72, 2 , 0 , 0 , 0 ,,
     3.5     3.5
   656.5   677.5
     3.5     3.5
   656.5   677.5
Pier Skew, UpSta & Num, DnSta & Num=  ,1501.39, 2 ,861.39, 2 , 0 , 0 , 0 ,,
     3.5     3.5
   658.1   677.5
     3.5     3.5
   658.1   677.5
BR Coef=-1 , 1 , 0 ,, 0 ,,,0.8,0,1.2,0,
WSPro=,,,, 1 ,,,, 0 ,,,, 0 ,,,,-1 ,-1 ,-1 , 0 , 0 , 0 , 0 , 0
BR U #Sta/Elev= 85
     .83  693.62   30.68  694.73   80.33  696.47  112.23  697.71  280.76  703.42
  303.85  704.07  359.11  704.82  398.99  705.47  409.48  705.58   478.8  706.51
  518.82  706.83  570.87  706.94   645.4  706.57  655.55  706.37  803.14  702.49
  803.16  702.78   823.7  702.12  868.66  700.54  907.58  699.11  983.58  695.63
 1028.88  693.49 1058.54  691.93 1098.55  690.01 1138.49  688.23 1178.05  686.64
 1218.21  685.34  1258.3  684.14 1298.23  683.08 1338.22  682.28  1388.2  681.54
 1432.93   681.1 1432.98   676.2  1440.5  671.46 1459.53  659.78 1466.24  656.28
 1483.45  653.06 1498.43  656.18 1499.42  656.18 1505.88  659.78 1529.88     676
 1531.41  676.28 1531.94  681.01 1562.42   681.2 1601.51  681.27 1654.93  681.23
 1743.63  681.33  1879.4  681.28 1963.85  681.09 1999.37  681.05 2069.37   680.8
    2114  680.72 2199.07  680.67 2259.36  680.67 2309.27  680.59 2409.36  680.53
 2464.39  680.53 2554.67  680.49 2669.34  680.35 2764.39   680.3  2964.4  680.51
 3134.12  680.44  3284.4  680.47 3354.25  680.51 3529.53   680.5 3644.29  680.43
 3829.07  680.46 3899.42  680.46 4029.28  680.32 4189.27  680.42 4427.41  680.42
 4487.43  680.41 4602.44  680.48 4691.73  680.58 4767.26  680.74  4842.2  680.96
 4897.23  681.05 4967.25  680.99  5115.9  681.09 5177.32   681.1 5359.67  681.02
 5482.43  681.04 5663.07  681.02 5767.55  681.06 5887.69  680.89 6084.55  680.26
BR U #Mann= 3
     .83     .12 1432.98    .045 1531.94     .12
BR U Banks=1432.98,1531.41
BR D #Sta/Elev= 73
     5.4  706.57   15.55  706.37  163.14  702.49  163.16  702.78   183.7  702.12
  228.66  700.54  267.58  699.11  343.58  695.63  388.88  693.49  418.54  691.93
  458.55  690.01  498.49  688.23  538.05  686.64  578.21  685.34   618.3  684.14
  658.23  683.08  698.22  682.28   748.2  681.54  792.93   681.1  792.98   676.2
   800.5  671.46  819.53  659.78  826.24  656.28  843.45  653.06  858.43  656.18
  859.42  656.18  865.88  659.78  889.88     676  891.41  676.28  891.94  681.01
  922.42   681.2  961.51  681.27 1014.93  681.23 1103.63  681.33  1239.4  681.28
 1323.85  681.09 1359.37  681.05 1429.37   680.8    1474  680.72 1559.07  680.67
 1619.36  680.67 1669.27  680.59 1769.36  680.53 1824.39  680.53 1914.67  680.49
 2029.34  680.35 2124.39   680.3  2324.4  680.51 2494.12  680.44  2644.4  680.47
 2714.25  680.51 2889.53   680.5 3004.29  680.43 3189.07  680.46 3259.42  680.46
 3389.28  680.32 3549.27  680.42 3787.41  680.42 3847.43  680.41 3962.44  680.48
 4051.73  680.58 4127.26  680.74  4202.2  680.96 4257.23  681.05 4327.25  680.99
  4475.9  681.09 4537.32   681.1 4719.67  681.02 4842.43  681.04 5023.07  681.02
 5127.55  681.06 5247.69  680.89 5444.55  680.26
BR D #Mann= 3
     5.4     .12  792.98    .045  891.94     .12
BR D Banks=792.98,891.41
BC Design=,, 0 ,, 0 ,,,,,,
BC Use User HTab Curves=0
BC User HTab FreeFlow(D)= 0

Type RM Length L Ch R = 1 ,100.00  ,17.76,17.86,21.41
BEGIN DESCRIPTION:
0.08 (I75 DS)
END DESCRIPTION:
#Sta/Elev= 30
       0  683.68   62.31   678.8   86.02   668.4   95.54  678.95  150.22  667.98
  825.26  664.61  833.12  661.85   859.6  652.79  884.26  660.39 1171.48  666.58
  1565.7  667.26 1852.98  662.52 2651.29   667.1 2728.36  677.68 2779.52  677.49
 2833.31  667.78 3012.95  665.49  3458.9  669.52 3522.46  677.17 3572.62  678.19
 3612.56   670.7 3712.67  668.48 4691.22  671.65 4802.05  681.65 4905.65  675.13
 5075.13  680.65 5213.19  672.41 5405.59   676.5 5474.73  700.34 5542.65  699.29
#Mann= 3 , 0 , 0
       0     .12       0  833.12    .045       0  884.26     .12       0
#XS Ineff= 4 ,-1
       0     510     685     510  774.83682.0837  900.61 2755.98 680.858
 2755.98 5573.72  701.34
Permanent Ineff=
       F       F       F       F
Bank Sta=833.12,884.26
XS Rating Curve= 0 ,0
Sediment Elevation=0
Exp/Cntr=0.5,0.3

Type RM Length L Ch R = 1 ,0.00    ,0,0,0
BEGIN DESCRIPTION:
0.08
END DESCRIPTION:
#Sta/Elev= 30
       0  683.67   65.65  678.64   90.89  667.99   98.55  680.53  112.01   667.3
  123.43   671.6  155.23  667.49  380.36  668.95  840.97  660.06  871.65  652.73
  896.56  659.87 1063.75  666.52  1715.6   661.4  2663.5  666.52 2717.54  677.39
 2764.75   677.2 2810.15  667.51 2931.55  665.11 3481.54  669.99 3588.29  677.79
 3654.92   668.4 4695.74  671.53 4825.64  681.73  4913.7  675.35 5058.82  680.86
 5145.19  672.47  5273.9  672.51 5413.67  676.92 5483.57  700.28 5557.24  699.55
#Mann= 3 , 0 , 0
       0     .12       0  840.97    .045       0  896.56     .12       0
#XS Ineff= 4 ,-1
       0  765.43683.1263  916.37 2721.89680.9581 2721.89 5526.91  700.94
 5526.91 5561.89680.9581
Permanent Ineff=
       F       F       F       F
Bank Sta=840.97,896.56
XS Rating Curve= 0 ,0
Exp/Cntr=0.3,0.1
Stream Node=RIVER-1         ,Reach-1         , 0 , 0 ,Upstream end
Stream Node=RIVER-1         ,Reach-1         , 0 , 1 ,Downstream end
LCMann Table=0

--- SpringCreek.g06 (geometry) ---

Geom Title=Proposed
Program Version=5.03

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
River Reach=RIVER-1         ,Reach-1

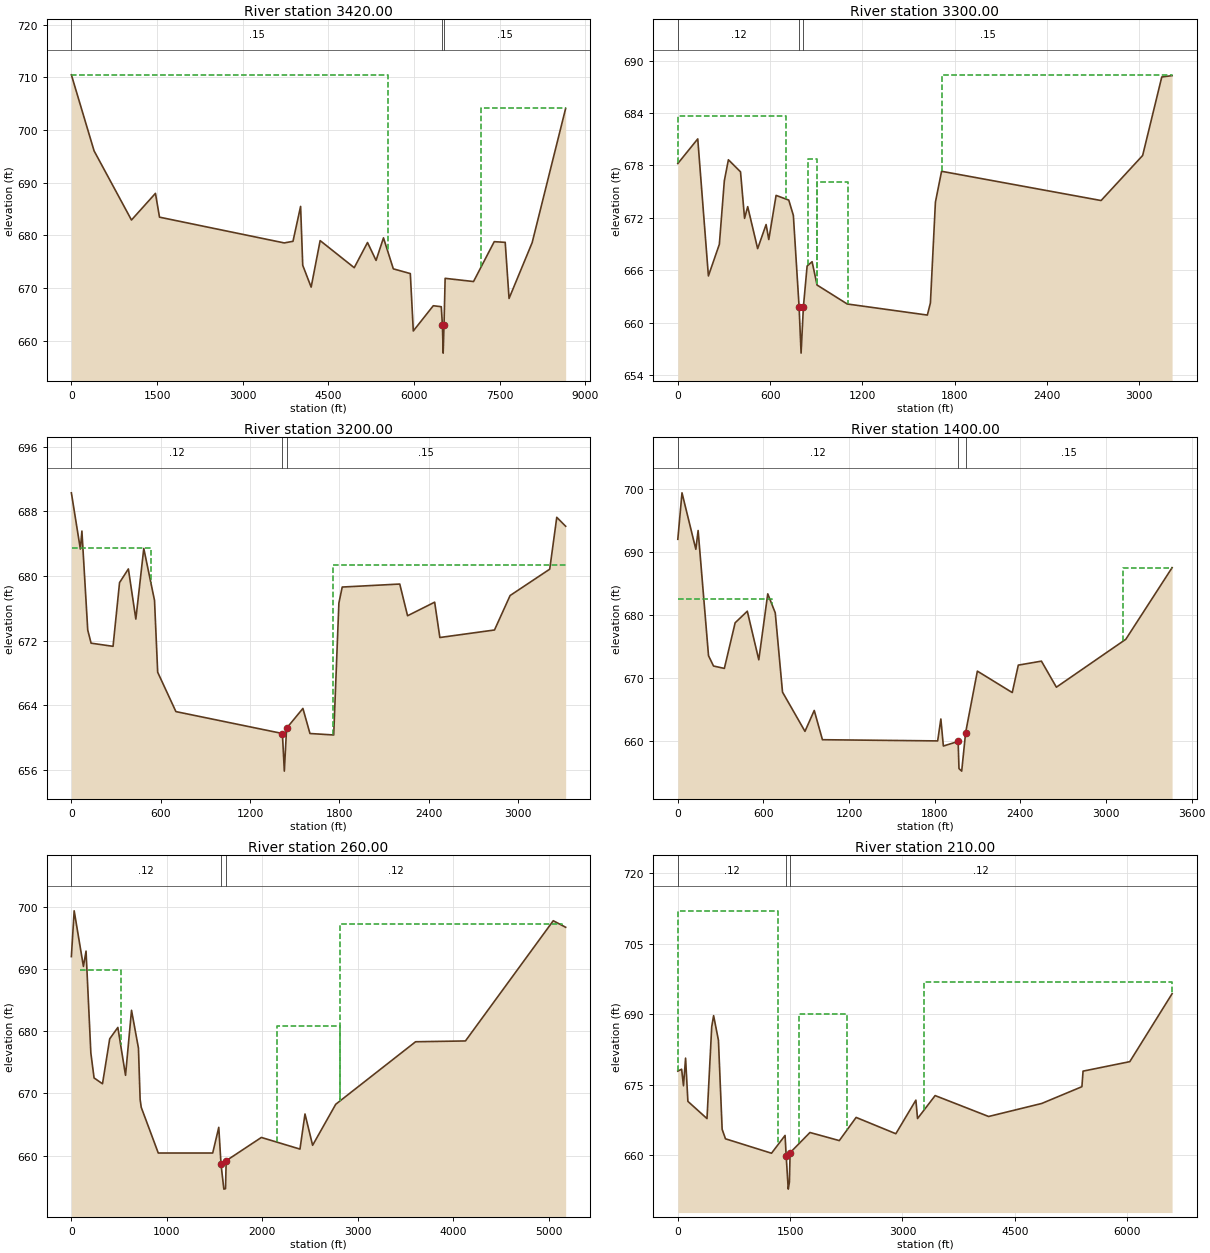
Type RM Length L Ch R = 1 ,3420.00 ,1149.97,1433.95,1398.9
BEGIN DESCRIPTION:
0.7 (C)
END DESCRIPTION:
#Sta/Elev= 30
       0  710.49   397.5  696.06  1052.5  682.93 1472.45  687.99 1543.66  683.47
 3728.79  678.58 3881.33  678.89 4014.78  685.51 4052.26  674.33 4199.68  670.19
  4357.1  679.02 4954.28  673.88 5186.66  678.66 5336.58  675.26 5466.51  679.54
 5638.93  673.66 5936.39  672.76 5988.88  661.87 6338.84  666.66 6478.83  666.47
 6498.82662.9615 6511.82657.6615 6526.82662.9615 6546.32  671.86 7043.76  671.25
  7406.2  678.82 7598.48  678.69 7665.91  668.04 8070.45  678.63 8657.27  704.12
#Mann= 3 , 0 , 0
       0     .15       0 6498.82    .045       0 6526.82     .15       0
#XS Ineff= 2 ,-1
       0 5547.66710.4872 7173.32 8657.27704.1202
Permanent Ineff=
       F       F
Bank Sta=6498.82,6526.82
XS Rating Curve= 0 ,0
Sediment Elevation=0
Exp/Cntr=0.5,0.3

Type RM Length L Ch R = 1 ,3300.00 ,676.12,766.4,761.35
BEGIN DESCRIPTION:
0.7 (Spring Creek Road DS)
END DESCRIPTION:
#Sta/Elev= 30
       0  678.22  129.59  681.04  198.86  665.34  270.04  668.97   302.4  676.24
   328.8  678.65  407.61  677.27  433.96  671.94  454.31  673.28     519  668.47
  573.93  671.23  591.41  669.51  638.85  674.57  721.25  674.03  751.14  672.28
  788.43   661.8  801.43   656.5  816.43   661.8  840.64  666.48  872.96  666.97
  905.28   664.3 1101.23  662.13 1622.24  660.86 1642.23  662.25 1674.71  673.79
 1714.68  677.33 2751.82  673.98 3021.96  679.14 3146.31  688.13 3213.46  688.29
#Mann= 3 , 0 , 0
       0     .12       0  788.43    .045       0  816.43     .15       0
#XS Ineff= 4 ,-1
 1716.27 3213.46  688.38    3.97   701.9 683.698  845.73  904.45   678.7
  904.45 1107.53  676.11
Permanent Ineff=
       F       F       F       F
Bank Sta=788.43,816.43
XS Rating Curve= 0 ,0
Sediment Elevation=0
Exp/Cntr=0.5,0.3

Type RM Length L Ch R = 1 ,3200.00 ,984.35,1233.17,1207.34
BEGIN DESCRIPTION:
0.7
END DESCRIPTION:
#Sta/Elev= 30
       0  690.29   60.29  683.34   70.73  685.56  109.96  673.32  132.46   671.7
  279.91  671.31  323.64  679.19  382.95  680.88  433.12  674.68  486.43  683.41
  558.57  676.99  579.82  668.11  702.28  663.24 1417.77  660.53 1430.77 655.879
 1445.77 661.179 1555.57  663.63 1602.91  660.53 1762.38  660.35 1797.26  676.66
 1819.68  678.64 2206.22  679.01 2258.59  675.09 2440.65  676.77 2475.61   672.4
 2842.67  673.33 2947.53  677.59 3213.78  680.85 3261.05  687.26 3320.77  686.16
#Mann= 3 , 0 , 0
       0     .12       0 1417.77    .045       0 1445.77     .15       0
#XS Ineff= 2 ,-1
    5.95  534.88683.5193 1757.28 3320.77681.3709
Permanent Ineff=
       F       F
Bank Sta=1417.77,1445.77
XS Rating Curve= 0 ,0
Sediment Elevation=0
Exp/Cntr=0.3,0.1

Type RM Length L Ch R = 1 ,1400.00 ,685.15,743.98,767.45
BEGIN DESCRIPTION:
0.32 (B)
END DESCRIPTION:
#Sta/Elev= 30
       0  691.98   29.27  699.33  126.25   690.4  142.19  693.37  215.11  673.56
     250  671.93  326.04  671.55  401.63  678.77  486.84   680.6  567.28  672.91
  630.14  683.35  682.66  680.34  733.51   667.8  890.84  661.59  955.77   664.9
 1013.21  660.27 1820.47  660.08 1842.96  663.55 1860.46  659.27  1963.9     660
  1969.9   655.7  1988.9   655.3 2016.45   661.4 2098.73  671.12 2343.08  667.73
 2385.47  672.07 2547.54   672.7 2652.27  668.58 3138.71  676.16    3463  687.49
#Mann= 3 , 0 , 0
       0     .12       0  1963.9    .045       0 2016.45     .15       0
#XS Ineff= 2 ,-1
 3120.78    3463687.4935       0  660.38682.5823
Permanent Ineff=
       F       F
Bank Sta=1963.9,2016.45
XS Rating Curve= 0 ,0
Sediment Elevation=0
Exp/Cntr=0.3,0.1

Type RM Length L Ch R = 1 ,260.00  ,340.4,327.95,308.81
BEGIN DESCRIPTION:
0.08 (A)
END DESCRIPTION:
#Sta/Elev= 30
       0  691.98   29.27  699.33  126.25   690.4  153.68  692.86  204.04  676.49
  237.76  672.49  326.04  671.55  401.63  678.77  486.84   680.6  567.28  672.91
  630.14  683.35   702.7  677.28  720.32  669.03  731.89  667.77  910.35  660.43
 1480.69  660.43 1544.25  664.55 1567.75  658.63 1597.52  654.63 1614.99   654.7
 1621.89  659.19 1990.49  662.93 2395.13  661.06 2447.58   666.7 2527.51  661.67
 2769.76  668.26 3606.31   678.3 4128.73  678.43  5048.6  697.74 5178.59  696.69
#Mann= 3 , 0 , 0
       0     .12       0 1567.75    .045       0 1621.89     .12       0
#XS Ineff= 5 ,-1
 2809.81 5135.17  697.28   95.24  517.01  689.89     6.8   95.24681.0101
 2149.66 2809.81680.7996 5135.17 5178.59680.7996
Permanent Ineff=
       F       F       F       F       F
Bank Sta=1567.75,1621.89
XS Rating Curve= 0 ,0
Sediment Elevation=0
Exp/Cntr=0.5,0.3

Type RM Length L Ch R = 1 ,210.00  ,326.2,320.77,313.61
BEGIN DESCRIPTION:
0.08 (I75 US)
END DESCRIPTION:
#Sta/Elev= 30
       0  677.88   50.81  678.29   75.73  674.77  103.57  680.65  134.43  671.45
  389.58  667.78  452.65  687.33  477.84  689.69  542.31  684.46  591.88   665.5
  636.41  663.48 1251.07  660.41 1432.08   664.2 1447.17  659.79 1474.44  652.77
  1489.9  654.21 1499.13  660.52  1764.3  664.82 2156.39   663.1 2380.94  668.03
 2911.17  664.56 3178.76  671.71  3200.9  667.79 3435.96  672.68 4150.11  668.23
 4858.96     671 5395.72  674.57  5411.1  677.88 6035.03   679.9 6600.01  694.36
#Mann= 3 , 0 , 0
       0     .12       0 1447.17    .045       0 1499.13     .12       0
#XS Ineff= 3 ,-1
       0 1342.82     712 1622.09    2260     690    3290 6600.01  696.82
Permanent Ineff=
       F       F       F
Bank Sta=1447.17,1499.13
XS Rating Curve= 0 ,0
Sediment Elevation=0
Exp/Cntr=0.5,0.3