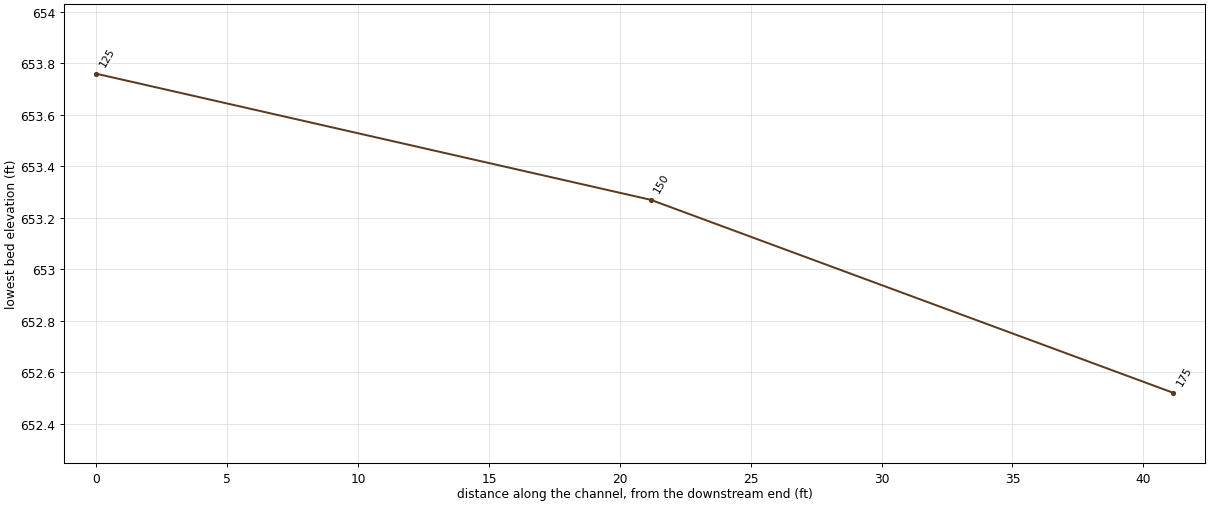
HEC-RAS study SpringCreek.prj: SpringCreek

--- SpringCreek.g06 (geometry) --- (continued)

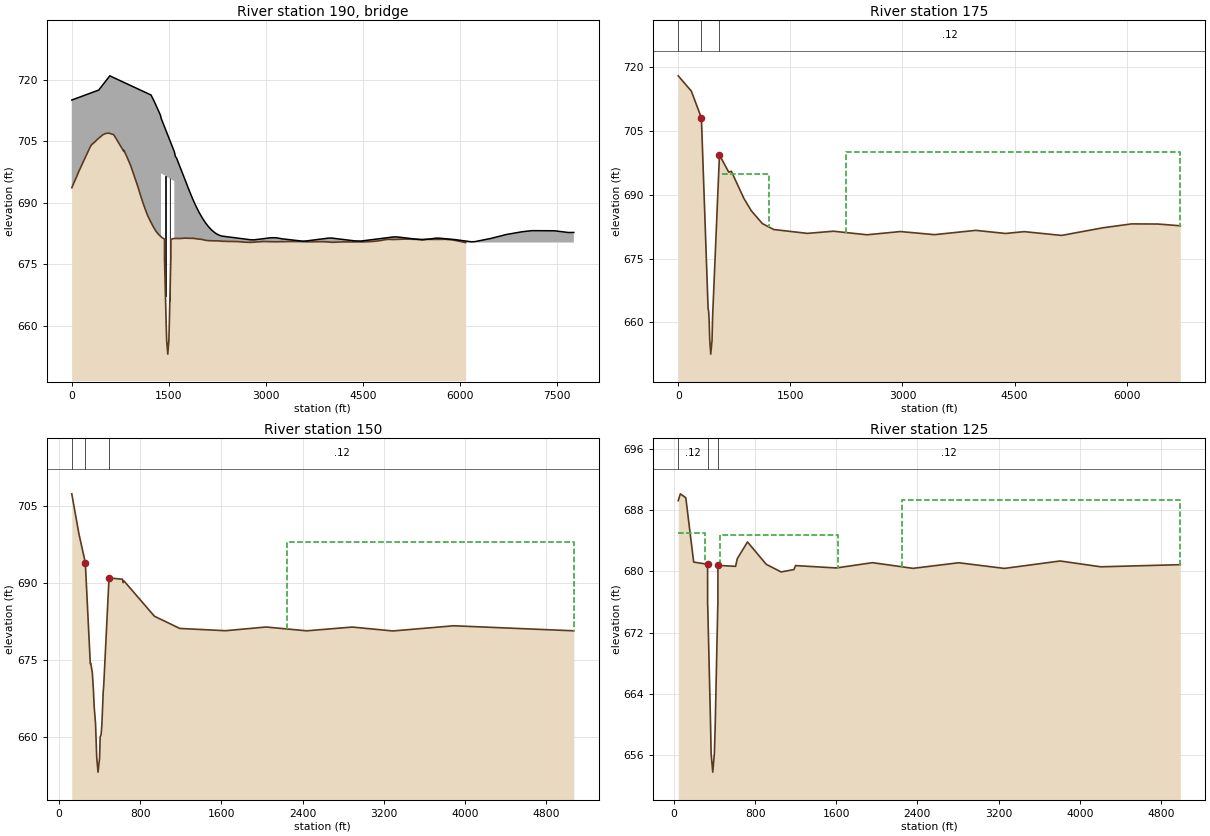
Type RM Length L Ch R = 3 ,190     ,,,
BEGIN DESCRIPTION:
I75
END DESCRIPTION:
Bridge Culvert--1,0,-1,-1, 0
Deck Dist Width WeirC Skew NumUp NumDn MinLoCord MaxHiCord MaxSubmerge Is_Ogee
74,230.2,2.6,0, 51, 49, , , 0.98, 0, 0,0,,
       0  416.53  587.38 1224.64 1273.71 1360.59 1377.08 1378.78 1378.78 1583.78
 1583.78 1603.16  1617.9 1818.23 1866.67 1916.67 1966.67 2015.44 2066.67 2116.67
 2165.72 2217.52 2266.68 2316.68  2766.7  2816.7 3064.87 3116.92 3167.04 3246.98
 3564.55 3617.23 3967.24 4011.61 4367.25 4467.26 4967.32 5019.46 5417.33 5617.36
 5667.38 5924.14 6167.66 6225.82 6468.37 6718.93 6952.72 7103.71  7455.9 7671.04
 7755.99
     715  717.43   720.9  716.22  714.67  711.65  710.91  710.62  710.62  702.43
  702.43  701.15   700.9   692.8  690.94  689.19  687.62  686.28  685.05  684.04
  683.23  682.57  682.12  681.84  680.93  680.92  681.41  681.44  681.41  681.17
   680.6  680.64  681.34  681.36  680.67  680.63  681.62  681.64  680.91  681.31
  681.34  680.97  680.45  680.48  681.24  682.24  682.88  683.16  683.13  682.71
  682.72
       0       0       0       0       0       0       0       0  697.14  695.24
       0       0       0       0       0       0       0       0       0       0
       0       0       0       0       0       0       0       0       0       0
       0       0       0       0       0       0       0       0       0       0
       0       0       0       0       0       0       0       0       0       0
       0
       0  185.28  234.35  321.23  337.72  339.42  339.42  544.42  544.42   563.8
  578.54  778.87  827.31  877.31  927.31  976.08 1027.31 1077.31 1126.36 1178.16
 1227.32 1277.32 1727.34 1777.34 2025.51 2077.56 2127.68 2207.62 2525.19 2577.87
 2927.88 2972.25 3327.89  3427.9 3927.96  3980.1 4377.97    4578 4628.02 4884.78
  5128.3 5186.46 5429.01 5679.57 5913.36 6064.35 6416.54 6631.68 6716.63
     718  716.22  714.67  711.65  710.91  710.62  710.62  702.43  702.43  701.15
   700.9   692.8  690.94  689.19  687.62  686.28  685.05  684.04  683.23  682.57
  682.12  681.84  680.93  680.92  681.41  681.44  681.41  681.17   680.6  680.64
  681.34  681.36  680.67  680.63  681.62  681.64  680.91  681.31  681.34  680.97
  680.45  680.48  681.24  682.24  682.88  683.16  683.13  682.71  682.72
       0       0       0       0       0       0  697.14  695.29       0       0
       0       0       0       0       0       0       0       0       0       0
       0       0       0       0       0       0       0       0       0       0
       0       0       0       0       0       0       0       0       0       0
       0       0       0       0       0       0       0       0       0
Pier Skew, UpSta & Num, DnSta & Num=  ,1447.36, 2 ,408, 2 , 0 , 0 , 0 ,,
       3       3
   656.5     698
       3       3
   656.5     698
Pier Skew, UpSta & Num, DnSta & Num=  ,1515.2, 2 ,475.84, 2 , 0 , 0 , 0 ,,
       3       3
   658.1     696
       3       3
   658.1     696
Abutment Skew #Up #Dn= , 3 , 3
 1378.78 1385.78 1435.86
  694.14  694.14   680.5
  339.42  346.42   396.5
  694.14  694.14   680.5
Abutment Skew #Up #Dn= , 3 , 3
  1526.7 1576.78 1583.78
   680.5  691.14  691.14
  487.34  537.42  544.42
   680.5  691.14  691.14
BR Coef=-1 , 1 , 0 ,, 0 ,,,0.8,0,1.2,0,
WSPro=,,,, 1 ,,,, 0 ,,,, 0 ,,,,-1 ,-1 ,-1 , 0 , 0 , 0 , 0 , 0
BR U #Sta/Elev= 85
     .83  693.62   30.68  694.73   80.33  696.47  112.23  697.71  280.76  703.42
  303.85  704.07  359.11  704.82  398.99  705.47  409.48  705.58   478.8  706.51
  518.82  706.83  570.87  706.94   645.4  706.57  655.55  706.37  803.14  702.49
  803.16  702.78   823.7  702.12  868.66  700.54  907.58  699.11  983.58  695.63
 1028.88  693.49 1058.54  691.93 1098.55  690.01 1138.49  688.23 1178.05  686.64
 1218.21  685.34  1258.3  684.14 1298.23  683.08 1338.22  682.28  1388.2  681.54
 1432.93   681.1 1432.98   676.2  1440.5  671.46 1459.53  659.78 1466.24  656.28
 1483.45  653.06 1498.43  656.18 1499.42  656.18 1505.88  659.78 1529.88     676
 1531.41  676.28 1531.94  681.01 1562.42   681.2 1601.51  681.27 1654.93  681.23
 1743.63  681.33  1879.4  681.28 1963.85  681.09 1999.37  681.05 2069.37   680.8
    2114  680.72 2199.07  680.67 2259.36  680.67 2309.27  680.59 2409.36  680.53
 2464.39  680.53 2554.67  680.49 2669.34  680.35 2764.39   680.3  2964.4  680.51
 3134.12  680.44  3284.4  680.47 3354.25  680.51 3529.53   680.5 3644.29  680.43
 3829.07  680.46 3899.42  680.46 4029.28  680.32 4189.27  680.42 4427.41  680.42
 4487.43  680.41 4602.44  680.48 4691.73  680.58 4767.26  680.74  4842.2  680.96
 4897.23  681.05 4967.25  680.99  5115.9  681.09 5177.32   681.1 5359.67  681.02
 5482.43  681.04 5663.07  681.02 5767.55  681.06 5887.69  680.89 6084.55  680.26
BR U #Mann= 3
     .83     .12 1338.22     .03 1562.42     .12
BR U Banks=1388.2,1562.42
BR D #Sta/Elev= 64
   17.17  691.93   57.18  690.01   97.12  688.23  136.68  686.64  176.84  685.34
  216.93  684.14  256.86  683.08  296.85  682.28  346.83  681.54  391.56   681.1
  391.61   676.2  399.13  671.46  418.16  659.78  424.87  656.28  442.08  653.06
  457.06  656.18  458.05  656.18  464.51  659.78  488.51     676  490.04  676.28
  490.57  681.01  521.05   681.2  560.14  681.27  613.56  681.23  702.26  681.33
  838.03  681.28  922.48  681.09     958  681.05    1028   680.8 1072.63  680.72
  1157.7  680.67 1217.99  680.67  1267.9  680.59 1367.99  680.53 1423.02  680.53
  1513.3  680.49 1627.97  680.35 1723.02   680.3 1923.03  680.51 2092.75  680.44
 2243.03  680.47 2312.88  680.51 2488.16   680.5 2602.92  680.43  2787.7  680.46
 2858.05  680.46 2987.91  680.32  3147.9  680.42 3386.04  680.42 3446.06  680.41
 3561.07  680.48 3650.36  680.58 3725.89  680.74 3800.83  680.96 3855.86  681.05
 3925.88  680.99 4074.53  681.09 4135.95   681.1  4318.3  681.02 4441.06  681.04
  4621.7  681.02 4726.18  681.06 4846.32  680.89 5043.18  680.26
BR D #Mann= 3
   17.17     .12  176.84     .03  490.57     .12
BR D Banks=346.83,560.14
BC Design=,, 0 ,, 0 ,,,,,,
BC Use User HTab Curves=0
BC User HTab FreeFlow(D)= 0

Type RM Length L Ch R = 1 ,175     ,21.09,19.96,18.91
BEGIN DESCRIPTION:
I75 US
END DESCRIPTION:
#Sta/Elev= 30
       0     718  175.62   714.4  309.88  708.09  399.83  663.11  406.19  662.81
  413.29  660.61  421.41  655.88  435.08  652.52  452.22  655.78  459.29  661.13
  551.51  699.38  675.62  695.34   710.9  695.54  877.31  689.19  977.31  686.25
 1126.36  683.23 1277.32  681.84 1727.34  680.93 2077.56  681.44 2525.19   680.6
 2972.25  681.36  3427.9  680.63  3980.1  681.64 4377.97  680.91 4628.02  681.34
  5128.3  680.45 5679.57  682.24 6064.35  683.16 6416.54  683.13 6716.63  682.72
#Mann= 3 , 0 , 0
       0     .12       0  309.88     .03       0  551.51     .12       0
#XS Ineff= 2 ,-1
     580    1215     695    2250 6716.63     700
Permanent Ineff=
       F       F
Bank Sta=309.88,551.51
XS Rating Curve= 0 ,0
Exp/Cntr=0.5,0.3

Type RM Length L Ch R = 1 ,150     ,20.55,21.18,21.91
#Sta/Elev= 30
  124.29  707.31  195.28  699.49   257.8  693.96  306.92  674.32  311.55   674.4
   327.1  672.58  338.06  669.12  344.62  666.15  358.64   662.7   370.4   656.1
  383.13  653.27  398.22  655.92  404.21  660.11  413.33  660.53   420.7  662.34
  434.75  669.03  438.91   669.9  491.61  690.98  624.29  690.72  631.38  690.07
  639.27  690.39  939.21  683.54 1189.43  681.17 1639.83  680.73 2040.04  681.45
 2440.05  680.71 2890.06  681.44 3290.07  680.68 3890.13  681.69 5074.36  680.71
#Mann= 3 , 0 , 0
  124.29     .12       0   257.8     .03       0  491.61     .12       0
#XS Ineff= 2 , 0
       0                    2250       0  698.03
Permanent Ineff=
       F       F
Bank Sta=257.8,491.61
XS Rating Curve= 0 ,0
Exp/Cntr=0.5,0.3

Type RM Length L Ch R = 1 ,125     ,132.15,129.81,127.38
#Sta/Elev= 30
   42.57  689.25   63.46  690.14  117.27  689.62  194.81  681.22   331.9  680.93
  332.11  675.87  333.76  675.29  361.54  659.84  366.56  656.22  383.03  653.76
  398.73  656.19  406.28  659.41  431.93  675.28  433.51  675.66  433.75  680.79
  607.94  680.66  624.48  681.66  725.26  683.85  909.86  680.93 1056.66  679.93
 1183.19  680.24 1199.09  680.76 1599.69  680.45  1957.2  681.14 2357.21   680.4
 2807.22  681.13 3257.23  680.39 3807.31  681.36 4207.32   680.6 4991.58  680.88
#Mann= 3 , 0 , 0
   42.57     .12       0   331.9     .03       0  433.75     .12       0
#XS Ineff= 3 ,-1
    2250 4991.58  689.35   42.57  309.86     685  455.57    1620   684.8
Permanent Ineff=
       F       F       F
Bank Sta=331.9,433.75
XS Rating Curve= 0 ,0
Exp/Cntr=0.5,0.3