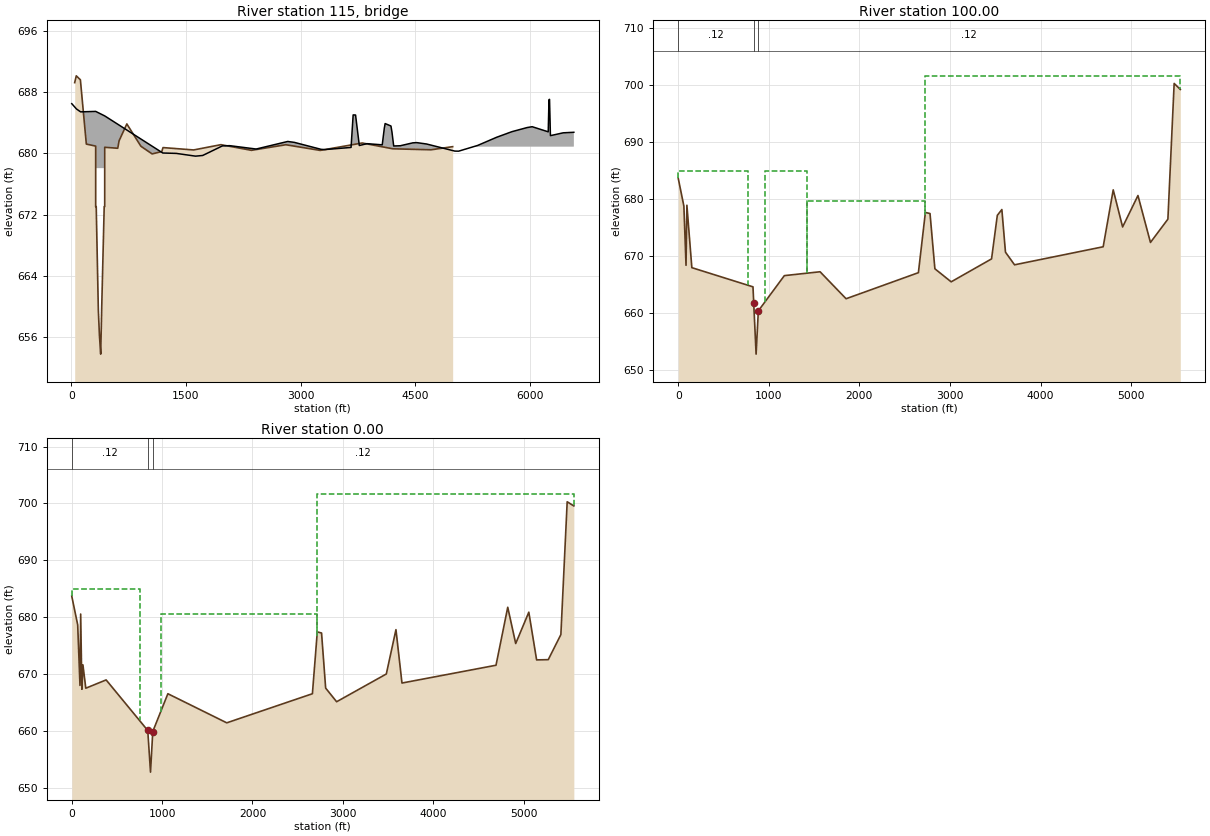
HEC-RAS study SpringCreek.prj: SpringCreek

--- SpringCreek.g06 (geometry) --- (continued)

Type RM Length L Ch R = 3 ,115     ,,,
Bridge Culvert--1,-1,-1,-1, 0
Deck Dist Width WeirC Skew NumUp NumDn MinLoCord MaxHiCord MaxSubmerge Is_Ogee
20,95,2.6,0, 48, 55, , , 0.98, 0, 0,0,,
    4.32   65.52  119.92  317.49  317.49  435.99  435.99  1196.4 1372.62 1625.11
  1718.9 1976.79 2072.08 2418.58 2832.05 2918.83 3268.99 3319.02 3661.07 3688.49
 3720.12 3769.23 3869.28 4069.37 4096.84 4107.28 4183.67 4197.34 4219.43 4306.27
 4469.54 4519.57 4649.17 5019.51 5069.36 5318.52 5567.72 5767.25 5967.07 6032.64
  6242.7 6252.43 6256.65 6259.95 6267.59 6271.51 6438.38 6578.16
   686.5  685.81  685.43  685.49  685.49   684.9   684.9  680.05     680  679.64
  679.73  680.98  681.01  680.57  681.56  681.44  680.53   680.5  680.78  685.03
  685.02  681.03  681.27  681.12  683.32   683.9  683.58  682.75  680.97     681
  681.38  681.41  681.23   680.3  680.29  681.04  682.11  682.84  683.38  683.49
  682.82     687  687.06  687.06  683.98  682.32  682.69  682.76
       0       0       0       0  678.07  678.07       0       0       0       0
       0       0       0       0       0       0       0       0       0       0
       0       0       0       0       0       0       0       0       0       0
       0       0       0       0       0       0       0       0       0       0
       0       0       0       0       0       0       0       0
       0   101.2  278.89  326.49  387.69  448.89  482.89  523.69  571.29  605.29
  802.86  802.86  921.36  921.36 1681.77 1857.99 2110.48 2204.27 2462.16 2557.45
 2903.95 3317.42  3404.2 3754.36 3804.39 4146.44 4173.86 4205.49  4254.6 4354.65
 4554.74 4582.21 4592.65 4669.04 4682.71  4704.8 4791.64 4954.91 5004.94 5134.54
 5504.88 5554.73 5803.89 6053.09 6252.62 6452.44 6518.01 6728.07  6737.8 6742.02
 6745.32 6752.96 6756.88 6923.75 7063.53
  698.94  696.29  690.98  689.68  688.26  687.11  686.59  686.08  685.64  685.43
  685.49  685.49   684.9   684.9  680.05     680  679.64  679.73  680.98  681.01
  680.57  681.56  681.44  680.53   680.5  680.78  685.03  685.02  681.03  681.27
  681.12  683.32   683.9  683.58  682.75  680.97     681  681.38  681.41  681.23
   680.3  680.29  681.04  682.11  682.84  683.38  683.49  682.82     687  687.06
  687.06  683.98  682.32  682.69  682.76
       0       0       0       0       0       0       0       0       0       0
       0  678.07  678.07       0       0       0       0       0       0       0
       0       0       0       0       0       0       0       0       0       0
       0       0       0       0       0       0       0       0       0       0
       0       0       0       0       0       0       0       0       0       0
       0       0       0       0       0
Abutment Skew #Up #Dn= , 3 , 3
  317.49   324.5  352.39
  673.04  673.04  659.44
  802.86  809.87  837.76
  673.04  673.04  659.44
Abutment Skew #Up #Dn= , 3 , 3
  396.42  428.99   435.7
  659.86  673.04  673.04
  881.79  914.36  921.07
  659.86  673.04  673.04
BR Coef=-1 , 0 , 0 ,, 0 ,,,0.8,0,2,0,
WSPro=,,,, 1 ,,,, 0 ,,,, 0 ,,,,-1 ,-1 ,-1 , 0 , 0 , 0 , 0 , 0
BR U #Sta/Elev= 30
   42.57  689.25   63.46  690.14  117.27  689.62  194.81  681.22  317.39  680.95
  317.39  673.04  324.49  673.04  352.39  659.44  366.56  656.22  383.03  653.76
  396.42  659.86  428.99  673.04   435.7  673.04   435.7   680.8  606.45  680.67
  624.48  681.66  725.26  683.85  909.86  680.93 1056.66  679.93 1183.19  680.24
 1199.09  680.76 1599.69  680.45  1957.2  681.14 2357.21   680.4 2807.22  681.13
 3257.23  680.39 3807.31  681.36 4207.32   680.6 4707.33  680.47 4991.58  680.88
BR U #Mann= 3
   42.57     .12  317.39     .03  606.45     .12
BR U Banks=317.39,435.7
BR D #Sta/Elev= 30
       0  683.68   62.31   678.8   86.02   668.4   95.54  678.95  150.22  667.98
  805.43  664.54  825.26  664.61   859.6  652.79  892.39  661.91  919.53  663.24
  1565.7  667.26 1900.22  662.57 2651.29   667.1 2728.36  677.68 2779.52  677.49
 2833.31  667.78 3012.95  665.49  3458.9  669.52 3522.46  677.17 3572.62  678.19
 3612.56   670.7 3712.67  668.48 4691.22  671.65 4802.05  681.65 4905.65  675.13
 5075.13  680.65 5213.19  672.41 5405.59   676.5 5474.73  700.34 5542.65  699.29
BR D #Mann= 3
       0     .12  805.43     .03  919.53     .12
BR D Banks=805.43,919.53
BC Design=,, 0 ,, 0 ,,,,,,
BC Use User HTab Curves=0
BC User HTab FreeFlow(D)= 0

Type RM Length L Ch R = 1 ,100.00  ,17.76,17.86,21.41
BEGIN DESCRIPTION:
0.08 (I75 DS)
END DESCRIPTION:
#Sta/Elev= 30
       0  683.68   62.31   678.8   86.02   668.4   95.54  678.95  150.22  667.98
  825.26  664.61  833.12  661.85   859.6  652.79  884.26  660.39 1171.48  666.58
  1565.7  667.26 1852.98  662.52 2651.29   667.1 2728.36  677.68 2779.52  677.49
 2833.31  667.78 3012.95  665.49  3458.9  669.52 3522.46  677.17 3572.62  678.19
 3612.56   670.7 3712.67  668.48 4691.22  671.65 4802.05  681.65 4905.65  675.13
 5075.13  680.65 5213.19  672.41 5405.59   676.5 5474.73  700.34 5542.65  699.29
#Mann= 3 , 0 , 0
       0     .12       0  833.12    .045       0  884.26     .12       0
#XS Ineff= 4 ,-1
 2724.72 5542.65  701.68       0  774.83     685     954    1420     685
    1420 2724.72  679.65
Permanent Ineff=
       F       F       F       F
Bank Sta=833.12,884.26
XS Rating Curve= 0 ,0
Sediment Elevation=0
Exp/Cntr=0.5,0.3

Type RM Length L Ch R = 1 ,0.00    ,0,0,0
BEGIN DESCRIPTION:
0.08
END DESCRIPTION:
#Sta/Elev= 30
       0  683.67   65.65  678.64   90.89  667.99   98.55  680.53  112.01   667.3
  123.43   671.6  155.23  667.49  380.36  668.95  840.97  660.06  871.65  652.73
  896.56  659.87 1063.75  666.52  1715.6   661.4  2663.5  666.52 2717.54  677.39
 2764.75   677.2 2810.15  667.51 2931.55  665.11 3481.54  669.99 3588.29  677.79
 3654.92   668.4 4695.74  671.53 4825.64  681.73  4913.7  675.35 5058.82  680.86
 5145.19  672.47  5273.9  672.51 5413.67  676.92 5483.57  700.28 5557.24  699.55
#Mann= 3 , 0 , 0
       0     .12       0  840.97    .045       0  896.56     .12       0
#XS Ineff= 3 ,-1
  2714.2 5557.24  701.68       0     750     685     985  2714.2   680.6
Permanent Ineff=
       F       F       F
Bank Sta=840.97,896.56
XS Rating Curve= 0 ,0
Exp/Cntr=0.3,0.1
Stream Node=RIVER-1         ,Reach-1         , 0 , 0 ,Upstream end
Stream Node=RIVER-1         ,Reach-1         , 0 , 1 ,Downstream end
LCMann Table=0